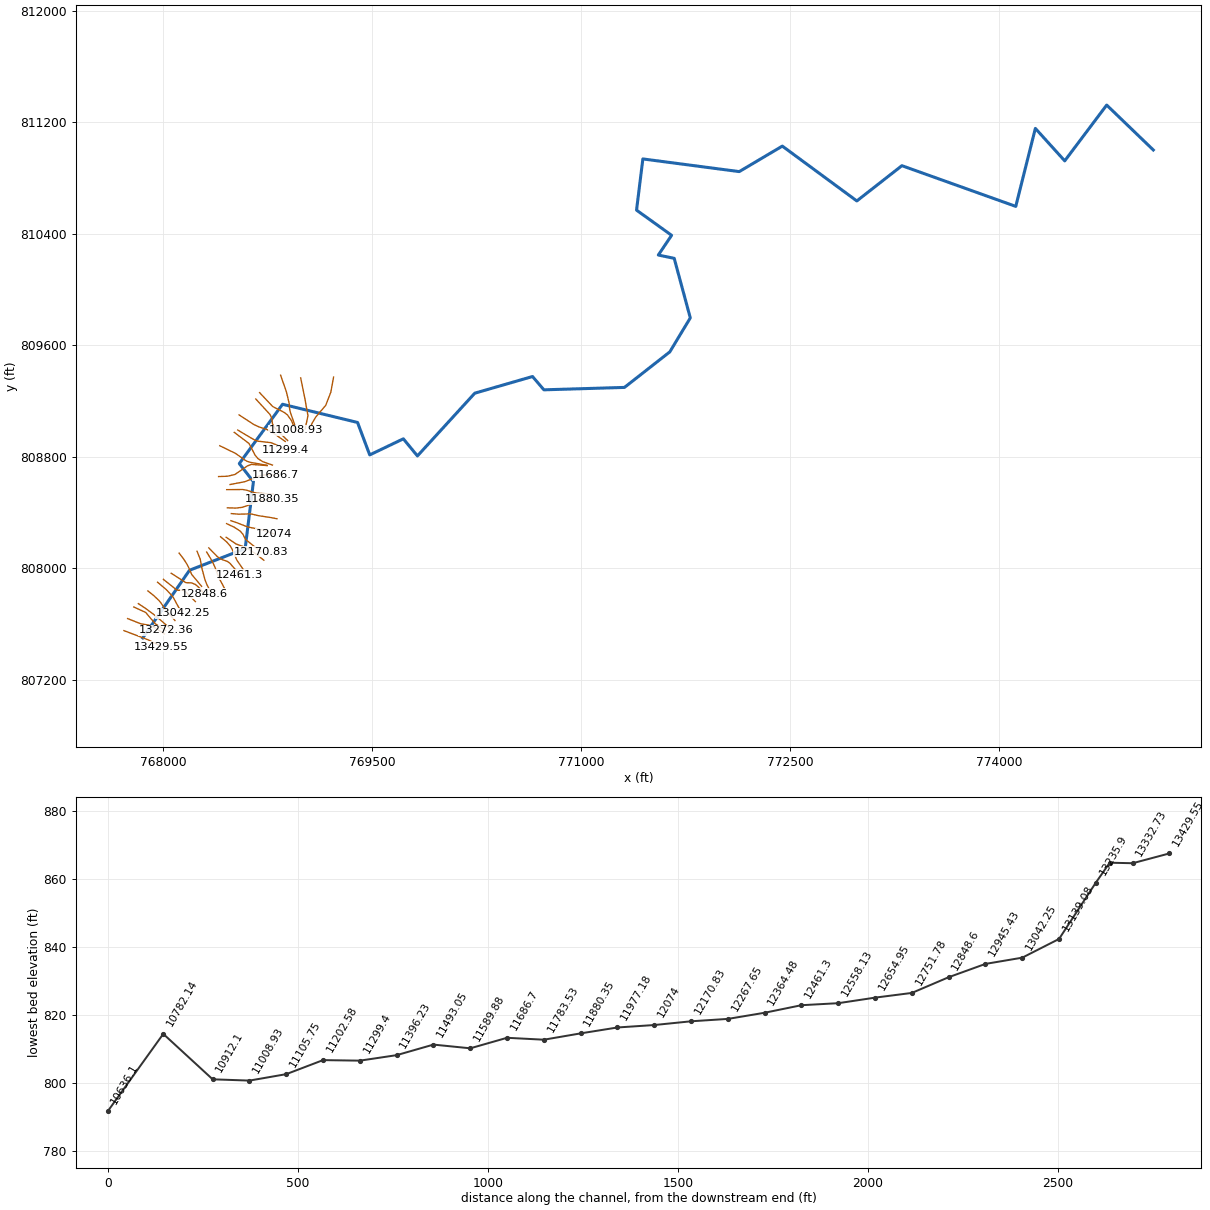
--- 17730_ras.prj (project) ---

Proj Title=17730
Current Plan=p01
Default Exp/Contr=0.3,0.1
English Units
Geom File=g01
Flow File=f01
Plan File=p01
Y Axis Title=Elevation
X Axis Title(PF)=Main Channel Distance
X Axis Title(XS)=Station
BEGIN DESCRIPTION:
RFD model 17730 exported to HEC-RAS
END DESCRIPTION:

--- 17730_ras.p01 (plan) ---

Plan Title=Plan 01
Program Version=4.10
Short Identifier=Plan 01
Geom File=g01
Flow File=f01
Subcritical Flow
Calc Critical at every XS
Secant Critical Depth

--- 17730_ras.f01 (steady flow) ---

Flow Title=Flow 01
Program Version=5.01
Number of Profiles= 6
Profile Names=10yr,25yr,50yr,100yr,100plus,500yr
River Rch & RM=17730,89,13429.55
   116.6  201.56  286.09  370.72  541.26  1074.4
River Rch & RM=17730,89,12654.95
  119.34  206.31  292.87  379.53  554.12 1096.43
River Rch & RM=17730,89, 12461.3
  120.84  208.93  296.61   384.4  561.22 1108.59
River Rch & RM=17730,89,12364.48
  122.65  212.09   301.1  390.24  569.75 1123.11
River Rch & RM=17730,89,12267.65
  130.64  226.02  321.02  416.17  607.61 1187.58
River Rch & RM=17730,89,12170.83
  132.41   229.1  325.43  421.91  615.98 1201.72
River Rch & RM=17730,89,   12074
  133.88  231.67  329.09  426.68  622.95 1213.45
River Rch & RM=17730,89,11977.18
  136.54  236.29  335.68  435.24  635.45 1234.46
River Rch & RM=17730,89,11783.53
  140.05  242.41  344.42   446.6  652.04 1262.25
River Rch & RM=17730,89,11589.88
  156.87  271.67  386.17  500.85  731.24 1393.39
River Rch & RM=17730,89,11396.23
  158.01  273.65     389  504.54  736.63 1402.25
River Rch & RM=17730,89, 11299.4
     160  277.12  393.95  510.98  746.03  1417.7
River Rch & RM=17730,89,11202.58
  162.83  282.06  401.01  520.16  759.43 1439.67
River Rch & RM=17730,89,11008.93
  163.96  284.03  403.82  523.82  764.77 1448.42
River Rch & RM=17730,89, 10912.1
  171.84  297.76  423.43  549.32  802.01  1509.1
River Rch & RM=17730,89,10782.14
  172.96   299.7  426.21  552.94  807.29 1517.69
River Rch & RM=17730,89, 10636.1
  178.83  309.92   440.8  571.91  834.99 1562.48
River Rch & RM=17730,89,10540.57
  181.87  315.22  448.38  581.77  849.39 1585.74
River Rch & RM=17730,89, 10349.5
  182.97  317.15  451.13  585.35  854.61 1594.16
River Rch & RM=17730,89,10226.94
  184.35  319.55  454.56  589.81  861.13 1604.67
River Rch & RM=17730,89,10025.32
  186.54  323.38  460.04  596.95  871.54 1621.42
River Rch & RM=17730,89,9776.299
  189.01  327.68  466.19  604.95  883.22 1640.19
River Rch & RM=17730,89,9585.232
  207.11  359.29  511.41  663.82  969.18 1777.38
River Rch & RM=17730,89,9394.165
  209.25  363.03  516.76  670.79  979.35 1793.48
River Rch & RM=17730,89,9203.098
  210.06  364.43  518.76  673.39  983.16  1799.5
River Rch & RM=17730,89,9107.564
     293  509.76   727.2  945.32 1380.16 2414.76
River Rch & RM=17730,89,9012.031
  294.49  512.37  730.93  950.18 1387.26 2425.48
River Rch & RM=17730,89,8820.964
  309.33  538.19  767.81   998.1 1457.22 2529.88
River Rch & RM=17730,89,8598.504
  316.18  550.18     785  1020.5 1489.94 2578.83
River Rch & RM=17730,89,8471.964
  324.96  565.43  806.75 1048.72 1531.13 2639.52
River Rch & RM=17730,89, 8376.02
  332.96  579.32  826.55 1074.39 1568.62 2694.53
River Rch & RM=17730,89,8280.077
  333.93  581.01  828.97 1077.55 1573.23 2701.37
River Rch & RM=17730,89, 8088.19
  336.36  585.26  835.05 1085.47 1584.79 2718.46
River Rch & RM=17730,89,7992.247
  337.08  586.52  836.87 1087.84 1588.24 2723.57
River Rch & RM=17730,89,7896.304
  341.01  593.36  846.63 1100.53 1606.78  2750.8
River Rch & RM=17730,89, 7800.36
  342.69   596.3  850.86 1106.03 1614.81 2762.68
River Rch & RM=17730,89,7512.528
  368.28  641.07  915.01 1189.61 1736.84 2941.83
River Rch & RM=17730,89,7272.575
  370.45  644.84   920.4 1196.63 1747.08  2956.7
River Rch & RM=17730,89, 7187.65
  371.87  647.32  923.96 1201.27 1753.85  2966.6
River Rch & RM=17730,89,7011.342
  372.11  647.75  924.57 1202.06    1755 2968.25
River Rch & RM=17730,89,6965.582
  383.46   667.6  953.01 1239.11  1809.1 3046.96
River Rch & RM=17730,89,6880.806
  386.14  672.24  959.63 1247.69 1821.62 3064.88
River Rch & RM=17730,89,6710.884
  386.38  672.67  960.23 1248.47 1822.76 3066.51
River Rch & RM=17730,89,6521.283
  392.26  682.83   974.7  1267.2 1850.11 3105.47
River Rch & RM=17730,89, 6423.88
  396.89  690.85  986.12 1281.98 1871.69 3136.17
River Rch & RM=17730,89,6131.669
  400.77  697.58   995.7 1294.39  1889.8 3161.94
River Rch & RM=17730,89,5839.458
  402.96  701.36 1001.09 1301.37 1899.99  3176.4
River Rch & RM=17730,89,5644.651
  411.86   716.8 1023.09 1329.89 1941.64 3235.57
River Rch & RM=17730,89,5449.843
  412.34  717.64 1024.28 1331.43 1943.89 3238.75
River Rch & RM=17730,89,4670.614
  402.47  700.52  999.89 1299.82 1897.73 3173.19
Boundary for River Rch & Prof#=17730,89,1
Up Type= 0
Dn Type= 2
Boundary for River Rch & Prof#=17730,89,2
Up Type= 0
Dn Type= 2
Boundary for River Rch & Prof#=17730,89,2
Up Type= 0
Dn Type= 2
Boundary for River Rch & Prof#=17730,89,2
Up Type= 0
Dn Type= 2
Boundary for River Rch & Prof#=17730,89,2
Up Type= 0
Dn Type= 2
Boundary for River Rch & Prof#=17730,89,2
Up Type= 0
Dn Type= 2

--- 17730_ras.g01 (geometry) ---

Geom Title=17730
Program Version=4.10

River Reach=17730,89
Reach XY= 30
 767854.06965363807500.631987989 768189.41242063807985.873955131
768588.562796205808141.046050891 768648.00957343808621.190777153
768546.546967208808751.230476603  768856.8911587809176.640745282
769394.866080344809046.168026105769482.354067713808813.299314931
769723.467631906808928.842844695769824.467968851808805.953644753
770235.720596641809256.045799375770650.203132987809375.738480449
770731.847527981809280.247960001771309.777340382809297.610173449
771635.148389727809552.514058545771782.070619434 809796.32645002
771666.572061658810223.546204537771552.611463279810247.196931377
771647.931121469810388.758699343 771396.44068554810569.251005813
771441.754918605810936.689771473772133.250478864810845.809913456
772442.298630744811028.705383152772976.723436564810635.299666494
773300.074458092810888.289863989774116.964643806810596.342681989
774257.547944576811155.737230748774468.206560791810922.848255262
774769.233236611811323.062724203775103.629413933811000.957479492

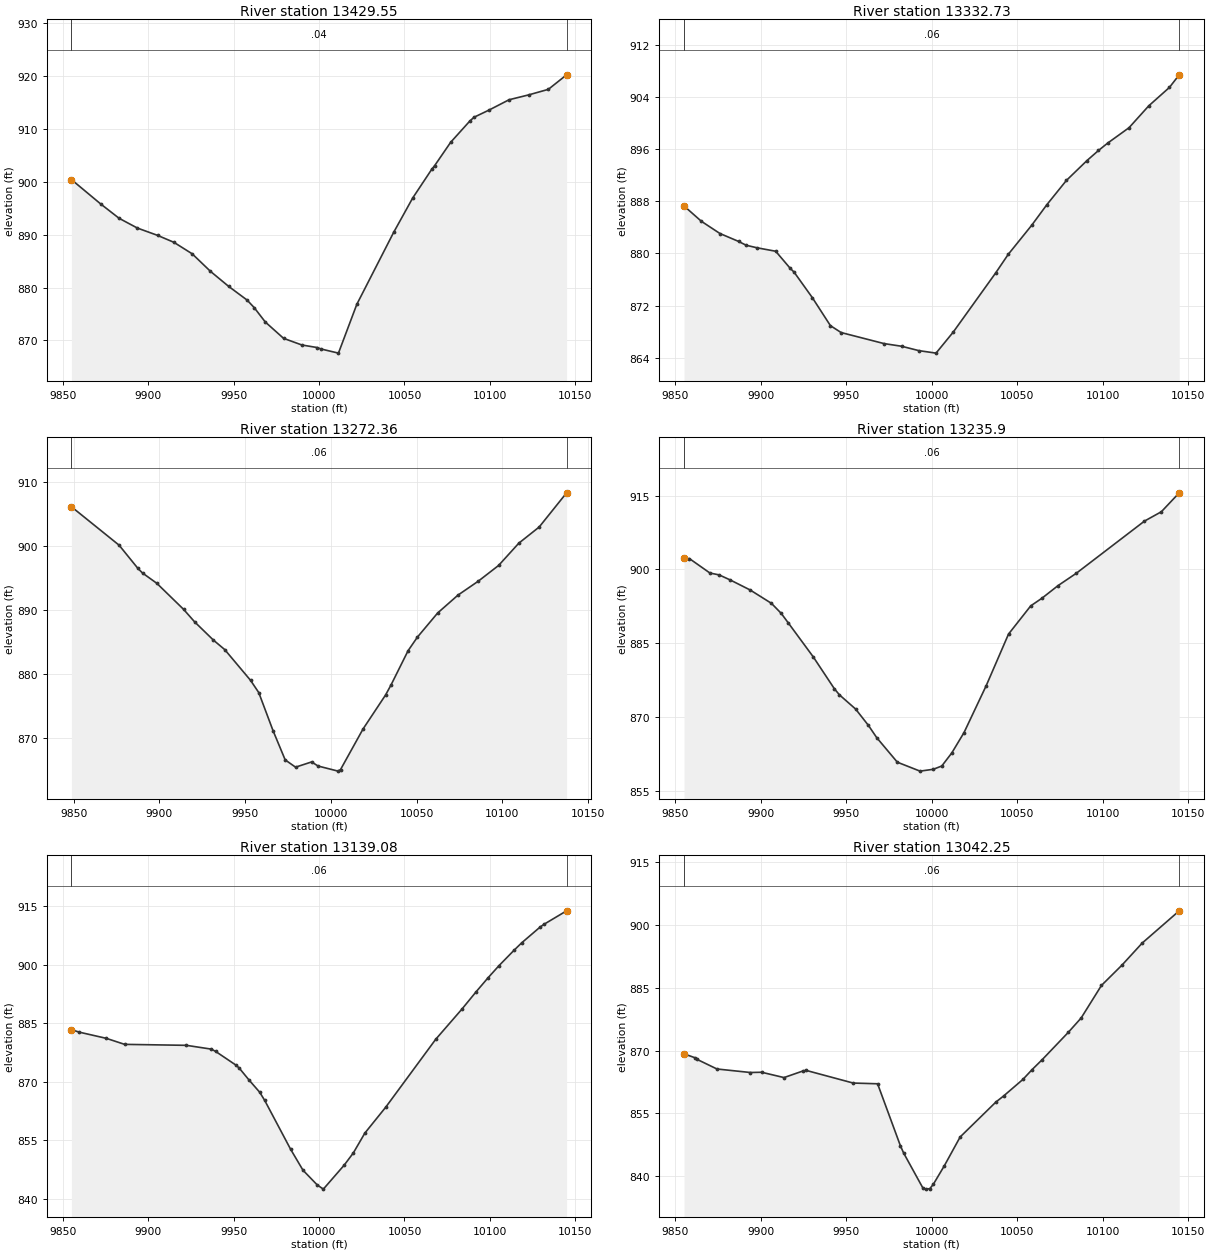
Type RM Length L Ch R = 1 ,13429.55,96.825200,96.825200,96.825200
XS GIS Cut Line= 6
767718.917631366807552.839138207767853.463135624807501.909538725
767855.347204376807501.238505985767893.048453851807486.390150625
 767942.57564027807462.437799351767984.205234242807437.925221824
#Sta/Elev= 30
9855.138900.42659872.334895.79529883.026893.10599893.719891.25779905.529 889.873
9915.104888.55719925.796886.38229936.489883.06579947.181880.20749957.873877.6426
9962.023876.22419968.566873.48179979.258870.39199989.951869.1347    9999 868.647
   10001  868.3910011.37 867.59410022.12876.833510043.69890.4569 10054.8 896.941
 10065.9902.350910067.68903.080610077.01907.479810088.12911.464310090.65912.2164
10099.35913.560110111.19915.532210122.56916.442310134.16 917.49810144.85920.2463
#Mann= 3 , 0 , 0
9855.138    0.04       09855.138    0.04       010144.85    0.04       0
#XS Ineff= 2 , 0
       0                               0
Bank Sta=9855.138,10144.85
Exp/Cntr=0.3,0.1

Type RM Length L Ch R = 1 ,13332.73,60.370300,60.370300,60.370300
XS GIS Cut Line= 6
767745.661931255807639.179266255 767838.71293499807602.220521349
767897.568339493807592.141848605767915.939825814807586.366548871
767955.972935496807564.870348401768009.764838246807528.580735789
#Sta/Elev= 29
9855.164887.29169865.307 884.9419876.168883.0651 9887.03881.8553 9891.49881.2663
9897.892880.87239908.753880.34559917.201877.73919919.545877.13189930.159873.2343
9940.773868.92379947.036867.86449972.111866.17219982.415865.76029992.493865.0895
10002.54 864.706 10012.6867.934510037.34876.985710044.73879.853910058.47 884.327
10067.43887.515510078.78891.212610090.78894.255310097.54895.809510102.84 896.929
10115.42899.308110126.96902.667610139.03905.489310144.77907.4247
#Mann= 3 , 0 , 0
9855.164    0.06       09855.164    0.06       010144.77    0.06       0
#XS Ineff= 2 , 0
       0                               0
Bank Sta=9855.164,10144.77
Exp/Cntr=0.3,0.1

Type RM Length L Ch R = 1 ,13272.36,36.454800,36.454800,36.454800
XS GIS Cut Line= 4
767789.707377282807722.307532348767874.926688281807683.200040303
767944.969957647807600.899198823768018.515390483807554.203685932
#Sta/Elev= 30
9848.614906.16039876.443900.15469887.445896.51999890.111895.80639898.448894.2005
9914.087890.12589920.454888.19079931.456885.32899938.063883.84649953.146879.0388
9957.921877.13329966.277871.1717 9973.35866.60979979.409865.47299988.779866.2923
 9992.54 865.65210004.21864.855510005.67865.1095 10018.8871.446510031.93876.7526
10035.07878.294110045.07 883.67210050.49885.783610062.33 889.56510074.18892.3554
10086.02894.530510097.87896.985910109.71900.476610121.56902.993310137.57908.3374
#Mann= 3 , 0 , 0
9848.614    0.06       09848.614    0.06       010137.57    0.06       0
#XS Ineff= 2 , 0
       0                               0
Bank Sta=9848.614,10137.57
Exp/Cntr=0.3,0.1

Type RM Length L Ch R = 1 , 13235.9,96.825200,96.825200,96.825200
XS GIS Cut Line= 6
767822.355899461807746.337346781767873.190169292807712.720123032
767924.846027468807674.903688475767941.198210114807661.910853256
767990.010273848  807621.2739066768050.245358026807568.080127399
#Sta/Elev= 30
9855.132902.23439858.302902.19999870.291899.27149875.686898.8934 9882.28897.8431
9893.814895.82739906.258893.11629911.943891.09069916.077 889.1589930.713882.2385
9943.106875.74339946.075874.5056  9955.5871.63239963.004868.30489967.893865.7999
9979.932860.8232 9993.21859.0067   10001859.381610005.95860.0542 10011.8862.7058
10018.96866.848110031.97 876.40710044.98886.858210057.99892.601310064.51894.1426
10073.99896.722810084.51899.188610124.54909.830610134.42 911.73110144.87915.5759
#Mann= 3 , 0 , 0
9855.132    0.06       09855.132    0.06       010144.87    0.06       0
#XS Ineff= 2 , 0
       0                               0
Bank Sta=9855.132,10144.87
Exp/Cntr=0.3,0.1

Type RM Length L Ch R = 1 ,13139.08,96.825100,96.825100,96.825100
XS GIS Cut Line= 6
767890.694192408807837.781218548767933.797221962807803.338564008
767969.130683445807769.853815243767984.648254708807751.085448466
768015.042120142807705.953305323768085.203715436 807625.12152622
#Sta/Elev= 30
9855.175883.3153 9859.63882.68519875.649881.07799886.288879.54189922.471879.2911
9937.009878.3186 9939.56 877.7259951.547874.17959953.338873.45729959.028870.4232
9965.326867.25669968.239865.16939983.381852.65799990.637847.2689    9999843.4843
10002.54 842.42310014.68848.543110020.09851.708510026.82856.788910039.06863.4469
10068.25880.8276 10083.5888.525710092.03893.087510098.76896.547210105.27899.7139
10114.01903.632510118.51905.552910129.27909.593210131.75910.361910144.84913.7799
#Mann= 3 , 0 , 0
9855.175    0.06       09855.175    0.06       010144.84    0.06       0
#XS Ineff= 2 , 0
       0                               0
Bank Sta=9855.175,10144.84
Exp/Cntr=0.3,0.1

Type RM Length L Ch R = 1 ,13042.25,96.825200,96.825200,96.825200
XS GIS Cut Line= 6
767960.269908163807899.997930464768022.046001879 807847.98404579
768063.718049911807803.524684271768075.828989726807786.034932876
768108.875294627807724.451710595768139.889804711807676.897939937
#Sta/Elev= 30
9855.152869.23449861.335868.33479862.912867.88639874.408865.61669893.964864.7777
9900.553864.83649913.626 863.5659925.016865.18389926.698865.26749954.116862.2563
9968.376862.08359981.676  847.339983.609845.54589994.933837.13919996.889 836.915
9998.944837.0282   10001838.081810007.38 842.46410016.68849.377310037.57 857.714
10042.04859.146810053.39863.123710058.72865.448910064.74 867.87210079.87874.3367
10087.44877.789110099.35885.581610111.28890.403910123.22895.717810144.84903.4029
#Mann= 3 , 0 , 0
9855.152    0.06       09855.152    0.06       010144.84    0.06       0
#XS Ineff= 2 , 0
       0                               0
Bank Sta=9855.152,10144.84
Exp/Cntr=0.3,0.1

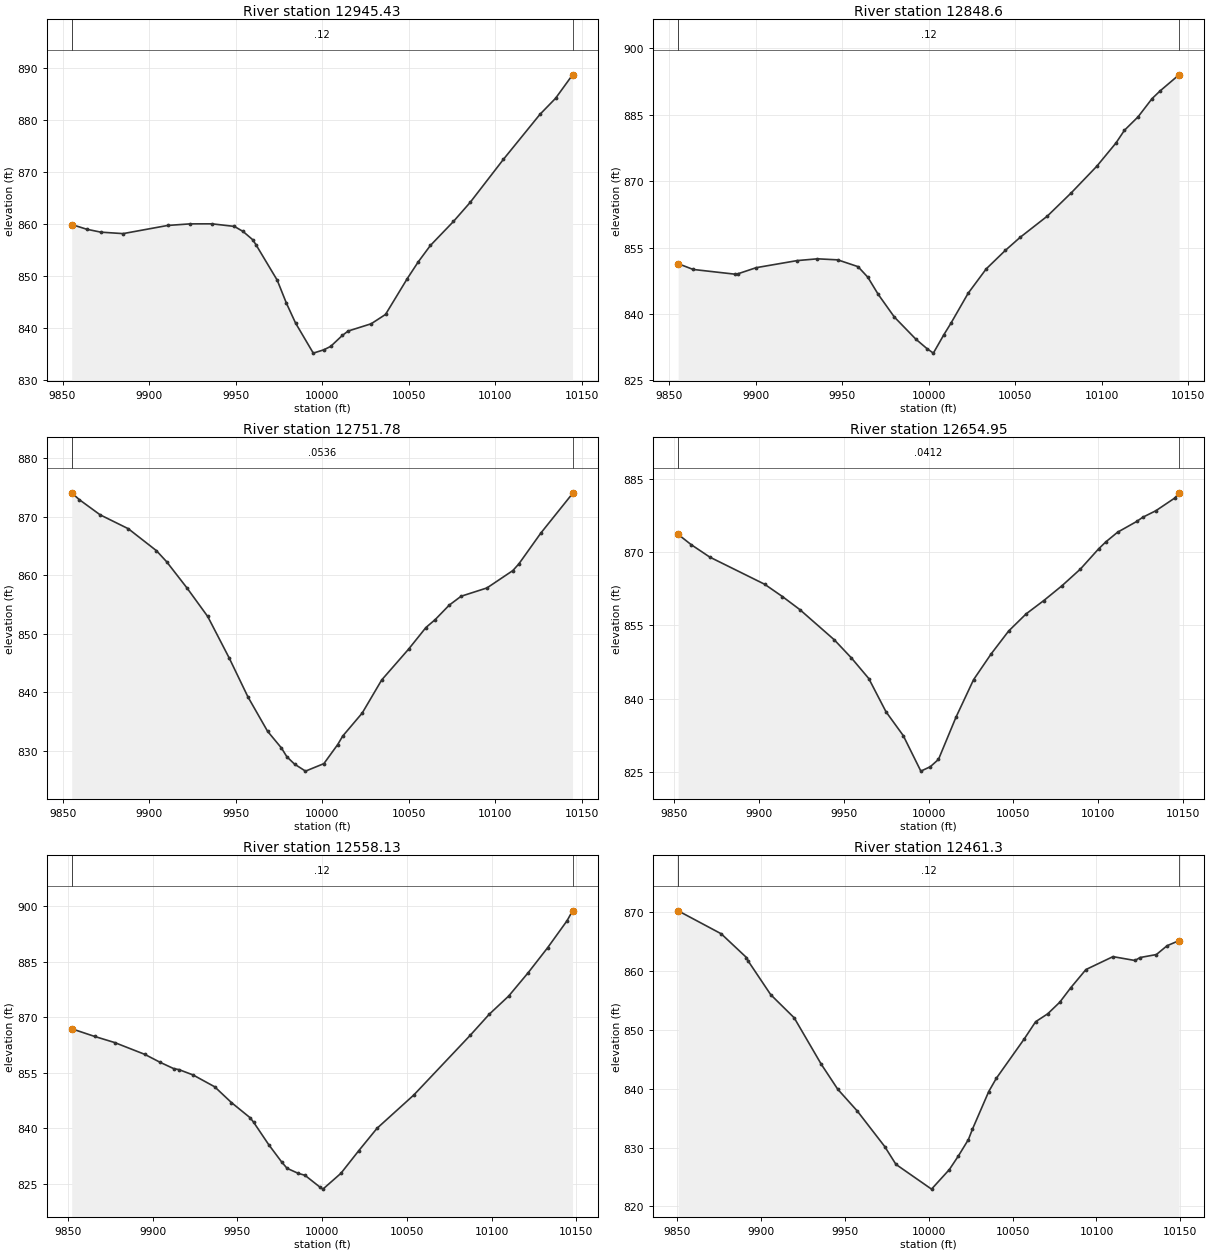
Type RM Length L Ch R = 1 ,12945.43,96.825100,96.825100,96.825100
XS GIS Cut Line= 6
 768001.91591492807920.492572687768095.360076387807846.507289879
768109.623402402 807841.86120271 768139.81515898807843.642284909
768159.206047951807834.285997572768231.517380059807760.897134282
#Sta/Elev= 30
9855.296859.85359864.032858.93529872.123858.38139884.984858.09769910.705859.6681
9923.565 859.9739936.426859.98229949.286859.4862 9954.33858.51219959.881 856.928
9961.793855.95659974.073849.12339979.382844.69299984.653 840.8799994.903835.0798
   10001835.719910004.97836.379810011.66838.478910015.05839.334810028.34840.7307
10036.64842.528210049.24849.441610055.57852.658510062.57855.811110075.89860.4319
10085.55864.102610104.77872.397610125.89881.066810134.92884.159110144.74888.6817
#Mann= 3 , 0 , 0
9855.296    0.12       09855.296    0.12       010144.74    0.12       0
#XS Ineff= 2 , 0
       0                               0
Bank Sta=9855.296,10144.74
Exp/Cntr=0.3,0.1

Type RM Length L Ch R = 1 , 12848.6,96.825200,96.825200,96.825200
XS GIS Cut Line= 6
768057.878962482 807964.53855288768162.942720457807897.012524855
768205.166799604807895.205442015768232.569638561807883.566990747
768261.996496936807857.399764342 768294.71761436 807816.51957738
#Sta/Elev= 30
9855.257851.3592 9863.91 850.0569888.214848.98419889.646849.05699900.365850.4604
9924.065852.05949935.774852.45689947.482852.22379959.191850.69289964.843848.3185
9970.899844.42319980.199839.31499992.624834.3199    9999832.203610002.74831.1639
10008.72835.254810012.81837.854810022.85844.679410033.29850.179210044.35854.3609
10052.93857.313810068.62862.101410082.53867.382810097.19873.351810108.26878.5917
10113.19881.479110121.07884.515110129.19888.647210133.88890.396810144.74894.0005
#Mann= 3 , 0 , 0
9855.257    0.12       09855.257    0.12       010144.74    0.12       0
#XS Ineff= 2 , 0
       0                               0
Bank Sta=9855.257,10144.74
Exp/Cntr=0.3,0.1

Type RM Length L Ch R = 1 ,12751.78,96.825100,96.825100,96.825100
XS GIS Cut Line= 6
768114.890747556808108.463377418768145.825533651808068.766379817
 768167.97562743808034.591227285768182.174778166808007.904382879
768205.504898542807955.033417868768276.444596467807870.582984535
#Sta/Elev= 30
9855.195874.05419859.586 872.8919871.641870.2973 9887.91867.92739904.179864.1793
 9910.01862.31749921.927857.78469933.843852.94039946.247845.86449957.112839.2058
9968.439833.35319976.476 830.4899979.605828.99859984.071827.73399990.379826.5414
10001.01827.821210009.01831.079110011.91832.532110023.18836.458610034.45842.1088
10050.04847.382110060.03851.061610065.42 852.42210073.48 854.87910080.36856.3979
10095.31857.815510110.25860.774510113.77861.925110126.48867.190810144.81873.9423
#Mann= 3 , 0 , 0
9855.195  0.0536       09855.195  0.0536       010144.81  0.0536       0
#XS Ineff= 2 , 0
       09988.378                       0
Bank Sta=9855.195,10144.81
Exp/Cntr=0.3,0.1

Type RM Length L Ch R = 1 ,12654.95,96.825200,96.825200,96.825200
XS GIS Cut Line= 6
768243.495573379808121.942421715768266.403074214808065.466501096
768279.771119596  807993.9848814768300.583367718807916.700622241
768314.359638801807882.286615279768334.922848172807842.851029726
#Sta/Elev= 30
9852.333873.60949859.987871.51839871.011868.9593 9903.32863.41019913.847860.8818
 9924.02858.23549944.367852.0435 9954.54848.30679964.714844.11419974.887837.3051
 9985.06 832.4299995.435825.1557   10001826.055910005.84827.561610016.18836.2139
10026.52843.871510036.87849.143210047.21853.836210057.55857.351810067.97 860.081
10078.74863.127610089.51866.513410100.28870.661410104.59872.101810111.42874.0526
 10122.7876.257710126.22877.108110133.98878.449210145.26881.077310147.68882.1224
#Mann= 3 , 0 , 0
9852.333  0.0412       09852.333  0.0412       010147.68  0.0412       0
#XS Ineff= 2 , 0
       0                               0
Bank Sta=9852.333,10147.68
Exp/Cntr=0.3,0.1

Type RM Length L Ch R = 1 ,12558.13,96.825100,96.825100,96.825100
XS GIS Cut Line= 6
768312.471262526808116.536240468768339.821053021808071.925410464
768359.025830397808036.305516328768371.828780738808008.011235748
768400.364570935807931.693974472768442.593009862807852.163621581
#Sta/Elev= 30
9852.281866.89999865.812864.82379877.542 863.1829895.384 859.9769904.608 857.787
9912.476856.11549915.521855.85569923.837 854.4139936.592851.21379946.508846.9358
9957.484842.85159959.567841.6327 9968.46835.57529976.131830.87049979.313829.1555
9985.962827.77599989.877827.2682    9999823.962910000.47 823.52210011.05827.7829
10021.63833.929310032.38839.976110054.07848.978510087.46865.178610098.62870.8413
10110.04875.745210121.52882.0455   10133888.807110144.47896.113710147.73898.8006
#Mann= 3 , 0 , 0
9852.281    0.12       09852.281    0.12       010147.73    0.12       0
#XS Ineff= 2 , 0
       0                               0
Bank Sta=9852.281,10147.73
Exp/Cntr=0.3,0.1

Type RM Length L Ch R = 1 , 12461.3,96.825200,96.825200,96.825200
XS GIS Cut Line= 6
768327.982511223808146.226679652 768390.90906007808081.672827997
768422.834505658808062.762231248 768459.97387347808049.776810082
768478.689968233808037.036587142 768549.41309983807954.426751195
#Sta/Elev= 30
9850.839870.22639876.466866.32529891.526  862.299892.602861.66549905.976855.9709
9919.949852.04429936.114844.13359945.903839.90039957.525836.20419973.863830.1672
 9980.56827.133910001.74822.929810012.36 826.25810017.64828.524910023.72831.3606
10026.13833.127810035.82839.514110040.28841.740210057.03848.481910063.75851.3823
10070.93852.721810078.14854.699510084.66857.151510093.71860.247610109.82862.4403
10122.92861.784910125.93 862.28810135.67862.794910142.05864.296810149.16865.1605
#Mann= 3 , 0 , 0
9850.839    0.12       09850.839    0.12       010149.16    0.12       0
#XS Ineff= 2 , 0
       0                               0
Bank Sta=9850.839,10149.16
Exp/Cntr=0.3,0.1

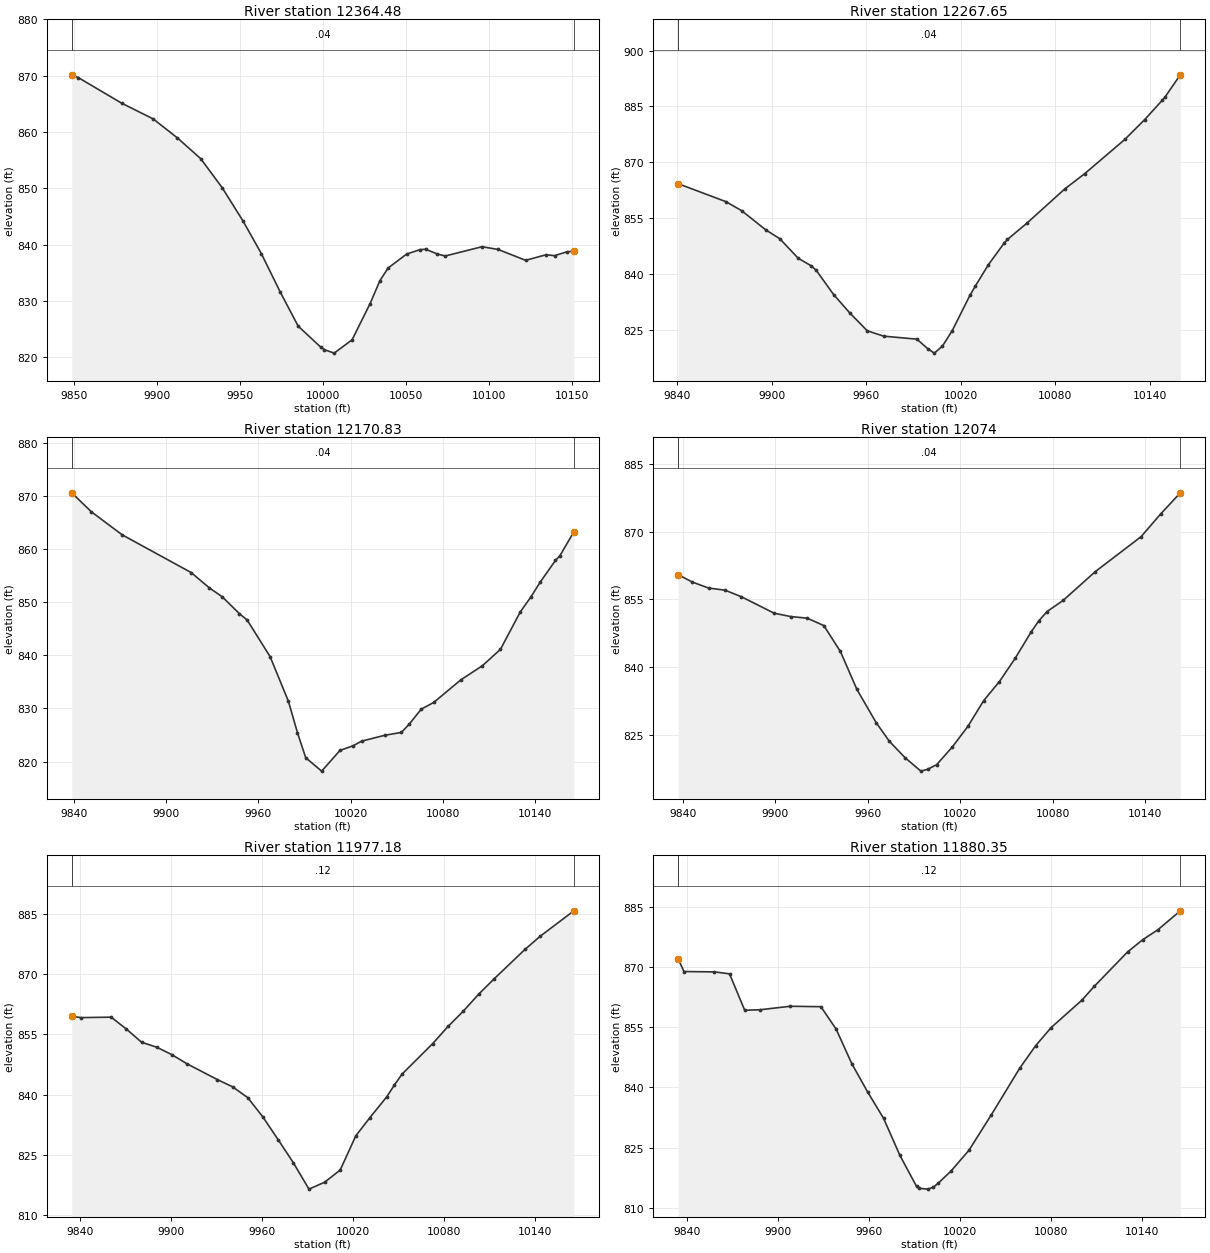
Type RM Length L Ch R = 1 ,12364.48,96.825100,96.825100,96.825100
XS GIS Cut Line= 6
768411.957470841808226.607525452768454.053413466808191.061990089
768481.561631402808160.526652453768494.665678401808137.814130119
768529.482886706808057.771082874768581.847297361807981.549276387
#Sta/Elev= 30
9848.856870.16619852.838869.66639879.014865.10749897.848862.34129912.448858.9608
9926.465855.27729939.361850.13969951.981844.19149963.026838.38919974.372831.5817
9985.212825.4991    9999821.7149   10001821.321210006.86820.710110017.65823.0745
10028.43829.471110034.45833.6128 10039.4835.851810050.58838.331410058.66839.1037
10061.93839.173510069.04838.321810073.73837.972810095.91839.621310105.62839.1311
10122.17837.202110134.54838.196910139.57838.028810146.92838.704210151.19 838.828
#Mann= 3 , 0 , 0
9848.856    0.04       09848.856    0.04       010151.19    0.04       0
#XS Ineff= 2 , 0
       0                               0
Bank Sta=9848.856,10151.19
Exp/Cntr=0.3,0.1

Type RM Length L Ch R = 1 ,12267.65,96.825200,96.825200,96.825200
XS GIS Cut Line= 6
768452.326462905808222.658313416768523.000831649808174.530730007
768580.512783519808153.997208978768620.877345345808133.482252701
768664.040418798808103.918808922768722.788398573 808057.89779442
#Sta/Elev= 30
 9840.51864.29949870.732859.50579880.771857.08679896.323851.86889904.972849.5851
9916.693844.34219925.171842.24929928.262 841.0479939.223834.60659949.347829.7413
9960.621824.88419971.063823.44189992.159822.6446    9999820.102510003.18818.8971
10008.29820.727410014.54824.876810025.89834.422810029.37 836.93610037.57842.5885
10047.58848.385410049.69849.366210061.81853.646510086.11862.906310098.81867.0087
10124.21876.151710136.92881.5086   10148886.636810149.62887.436710159.51893.4847
#Mann= 3 , 0 , 0
 9840.51    0.04       0 9840.51    0.04       010159.51    0.04       0
#XS Ineff= 2 , 0
       0                               0
Bank Sta=9840.51,10159.51
Exp/Cntr=0.3,0.1

Type RM Length L Ch R = 1 ,12170.83,96.825200,96.825200,96.825200
XS GIS Cut Line= 6
768455.352312982808320.402595639768510.101687372808294.740609631
768550.909363836808268.420533165 768572.15473175808245.321643278
768590.562753022808208.097903594 768702.02096045808117.468310252
#Sta/Elev= 30
9838.715870.54519851.445866.98479871.458862.65229916.386855.54669928.197852.6635
 9936.54850.99589947.801847.80349952.798 846.6179967.687839.74689979.635831.3295
9985.523825.40059990.867  820.7210001.24818.193910013.14822.0834 10021.6822.9566
10027.32823.840410042.38824.943210053.09825.473510058.23827.044310065.97829.8414
10074.09831.107310091.75835.362310105.79838.021310117.53841.109610130.42848.1419
10137.48851.018810143.32853.728410153.32857.834410156.21858.722310165.26863.2093
#Mann= 3 , 0 , 0
9838.715    0.04       09838.715    0.04       010165.26    0.04       0
#XS Ineff= 2 , 0
       0                               0
Bank Sta=9838.715,10165.26
Exp/Cntr=0.3,0.1

Type RM Length L Ch R = 1 ,   12074,96.825100,96.825100,96.825100
XS GIS Cut Line= 6
 768486.32656649808341.455711114768531.581689116808325.894386342
768606.623995339808296.639177544768701.389047458808277.451675143
768751.798234762808262.581915867768797.067127864 808246.46265566
#Sta/Elev= 30
9837.156860.46889846.328858.84229856.903857.51829867.477857.06089878.052855.6142
9899.414851.96519910.147851.2242 9920.88850.87039931.613849.22949942.346843.5194
9953.079  835.139965.555 827.802 9974.11823.68529984.322820.05779994.535817.0947
    9999817.507110004.74818.507610014.93822.417710025.13827.018710035.33832.6826
10045.53836.881210055.73842.010710066.01847.786410070.91850.228410076.43852.3362
10086.86854.800110107.71861.1537 10137.4868.868610150.04873.864110162.85878.5511
#Mann= 3 , 0 , 0
9837.156    0.04       09837.156    0.04       010162.85    0.04       0
#XS Ineff= 2 , 0
       0                               0
Bank Sta=9837.156,10162.85
Exp/Cntr=0.3,0.1

Type RM Length L Ch R = 1 ,11977.18,96.825200,96.825200,96.825200
XS GIS Cut Line= 6
768489.123382807808392.394257843768541.004261582 808388.25354002
768630.603141898808390.115472182 768683.98091315808377.405705401
768769.004580466808364.627458475768816.649242489808355.183449206
#Sta/Elev= 30
9834.464859.5851 9840.36859.21599860.423859.33299870.455856.36929880.487853.0698
9890.509851.82439900.515849.96029910.521847.66779930.533843.7297 9940.54841.9285
9950.546839.22349960.552834.37869970.559828.74129980.665822.92899990.897816.3755
10001.19818.093910011.49821.1394 10021.8829.698410031.05 834.21410042.19839.4342
10047.24842.358510052.31845.114810072.53852.735110082.64857.013910092.75860.8528
10102.87865.083310112.98 868.88610133.34 876.24310143.53879.5811 10165.6885.8902
#Mann= 3 , 0 , 0
9834.464    0.12       09834.464    0.12       0 10165.6    0.12       0
#XS Ineff= 2 , 0
       0                               0
Bank Sta=9834.464,10165.6
Exp/Cntr=0.3,0.1

Type RM Length L Ch R = 1 ,11880.35,96.825100,96.825100,96.825100
XS GIS Cut Line= 6
768461.241206347808433.744216223768522.289649503808431.924926847
768567.003604617808437.294645959768606.371096056808450.186231496
768682.402137043808488.526509266768779.748111586808496.914919044
#Sta/Elev= 30
9834.443 871.985 9838.21868.82069858.255 868.7359868.262868.24729878.262859.1899
9888.262859.29879908.353860.17619928.497860.06679938.569854.47279948.872845.8871
9959.234838.88789969.852832.25639980.601 823.0339991.604 815.2979993.417814.8298
    9999814.640110002.71 815.14610005.98816.148710014.36819.162810026.13  824.32
10040.95 833.19310059.59844.745510070.15850.3859 10080.3854.8665 10100.6861.6958
10108.74 865.12610130.72873.712210140.72876.753110150.73879.235210165.48883.9392
#Mann= 3 , 0 , 0
9834.443    0.12       09834.443    0.12       010165.48    0.12       0
#XS Ineff= 2 , 0
       0                               0
Bank Sta=9834.443,10165.48
Exp/Cntr=0.3,0.1

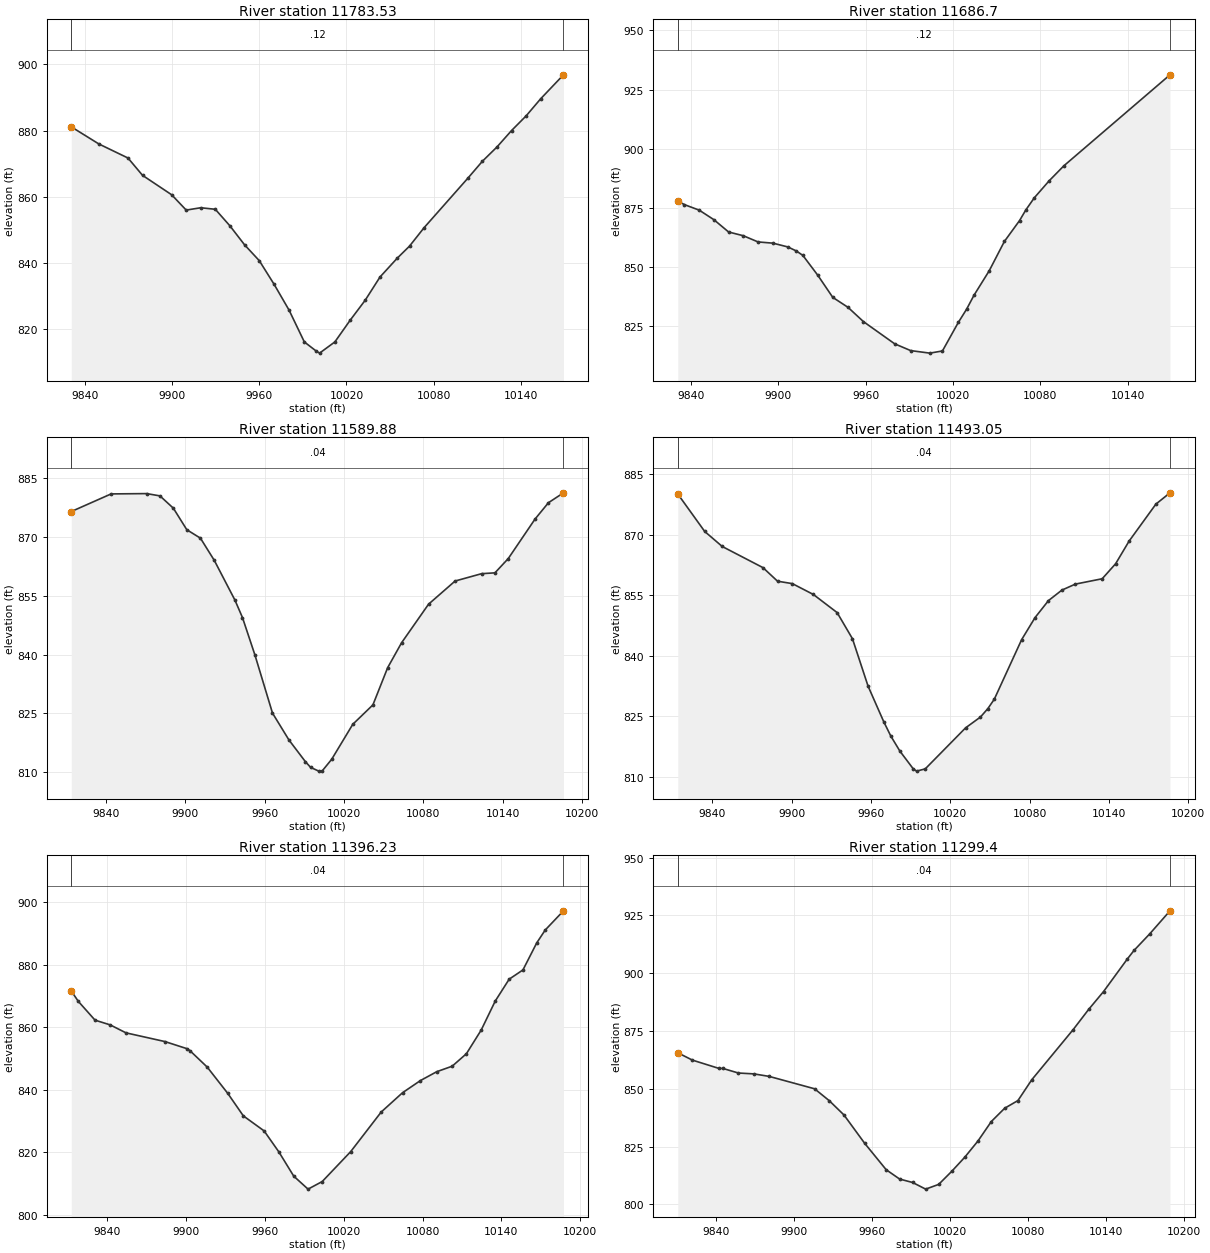
Type RM Length L Ch R = 1 ,11783.53,96.825200,96.825200,96.825200
XS GIS Cut Line= 6
768456.028575092808564.044203757768570.241868227808565.211402932
768598.568983807 808560.28025226768648.439697517808544.501415012
768676.593397313808538.631888453768790.652089393808531.890608591
#Sta/Elev= 30
9830.812881.14179849.792875.96829869.802871.72639879.807866.49019899.816860.6253
9909.821855.99249919.829856.70189929.838856.23319939.847851.24849949.924845.5146
9960.074840.70749970.224833.59769980.575825.74299991.037816.1599    9999813.4712
10001.53812.777510012.04816.168310022.54 822.71110032.86828.743910043.07 835.778
10054.92841.467210063.36845.1101 10073.4850.689610103.48 865.63810113.49870.7608
 10123.5 875.07210133.51 880.02810143.52884.454210153.53889.6278 10169.2896.8586
#Mann= 3 , 0 , 0
9830.812    0.12       09830.812    0.12       0 10169.2    0.12       0
#XS Ineff= 2 , 0
       0                               0
Bank Sta=9830.812,10169.2
Exp/Cntr=0.3,0.1

Type RM Length L Ch R = 1 , 11686.7,96.825100,96.825100,96.825100
XS GIS Cut Line= 6
768480.443309559808600.834686233768587.693478711 808621.47114936
768673.841241827808656.560284999768709.183050069808667.012601884
768751.028967315808672.174145335768807.741380399808668.934342945
#Sta/Elev= 30
9830.817877.76289835.425876.23149845.537873.90379855.649869.85749865.761864.6486
9875.874863.06419885.986860.43749896.235859.92029906.518858.30789912.338856.6004
  9916.8854.73249927.083846.29489937.365836.94739947.851832.72429958.413826.6979
 9979.89817.28839990.906814.411110004.05813.340410012.73814.259410023.62826.3157
10029.31831.912310034.46837.895610044.88848.224210055.31860.646110065.74869.4866
 10070.1874.037410075.96879.194810086.04886.307910096.11892.633610169.13931.2195
#Mann= 3 , 0 , 0
9830.817    0.12       09830.817    0.12       010169.13    0.12       0
#XS Ineff= 2 , 0
       0                               0
Bank Sta=9830.817,10169.13
Exp/Cntr=0.3,0.1

Type RM Length L Ch R = 1 ,11589.88,96.825200,96.825200,96.825200
XS GIS Cut Line= 6
768398.071519862808658.034121174768462.486173694808660.494115772
768515.620570898808673.150168877768604.531421899808734.225818578
768633.683654714808745.106495151768746.192953404808736.846383192
#Sta/Elev= 30
9813.831876.49429843.969 880.9959870.839881.0759  9880.9880.49169891.055877.3436
9901.211871.85579911.529869.69849921.971864.04989937.608853.89599943.328849.4258
9952.735839.89379966.025825.05689978.461818.20169990.818812.70329994.783811.2212
   10001810.246510003.56810.2744 10010.8813.269710026.75822.196510041.99827.1597
10053.13 836.64810063.66843.007310084.07852.852610104.14858.7626 10124.2860.6396
10134.27860.850510144.34864.494710164.57874.562810174.73878.748410186.11881.2722
#Mann= 3 , 0 , 0
9813.831    0.04       09813.831    0.04       010186.11    0.04       0
#XS Ineff= 2 , 0
       0                               0
Bank Sta=9813.831,10186.11
Exp/Cntr=0.3,0.1

Type RM Length L Ch R = 1 ,11493.05,96.825100,96.825100,96.825100
XS GIS Cut Line= 6
768406.511339361808879.143219743768519.321174472808824.378112178
768588.288828098808775.454226267768603.745667505808766.984661235
768627.389687828808759.830892082768745.489303738808738.772857805
#Sta/Elev= 30
9813.781880.15949834.159870.8522 9847.42  867.129878.245861.86779889.266 858.498
9900.454857.90019916.365855.20519934.337850.70629945.932844.21529957.757832.4327
9969.582823.62089974.974820.03459981.826816.30539991.908811.9131 9994.42811.3364
   10001811.893110031.52822.0784 10042.8824.777210048.35826.855310053.25829.1949
10073.92843.981610084.08849.467610094.24853.6872 10104.4856.293810114.56857.7771
10134.87859.107210145.03862.834510155.19 868.439 10175.5877.641710186.16880.4464
#Mann= 3 , 0 , 0
9813.781    0.04       09813.781    0.04       010186.16    0.04       0
#XS Ineff= 2 , 0
       0                               0
Bank Sta=9813.781,10186.16
Exp/Cntr=0.3,0.1

Type RM Length L Ch R = 1 ,11396.23,96.825200,96.825200,96.825200
XS GIS Cut Line= 6
768510.602493509808975.209423913768616.599101778808895.060421829
768658.660879708808813.872235139768680.420769918808786.687737562
768717.441932971808763.578430404768784.406402632 808740.81510437
#Sta/Elev= 30
9812.679871.64329818.006868.32529830.769862.29699842.232 860.7959854.346858.2336
9883.928855.4533 9901.08853.12639903.223852.45049916.144847.28039931.793838.8662
9943.626831.67659959.452826.86279970.644820.16369982.021812.3741 9992.89808.2322
10003.68810.661210025.36820.239810048.56832.899610064.79839.073710078.43842.9712
10090.83845.804810102.58847.5642 10113.4851.548710124.64859.103310135.36868.4067
10145.97875.409810156.46878.373710166.94887.0169 10173.4891.1372 10187.3897.2807
#Mann= 3 , 0 , 0
9812.679    0.04       09812.679    0.04       0 10187.3    0.04       0
#XS Ineff= 2 , 0
       0                               0
Bank Sta=9812.679,10187.3
Exp/Cntr=0.3,0.1

Type RM Length L Ch R = 1 , 11299.4,96.825100,96.825100,96.825100
XS GIS Cut Line= 6
768535.510122482808991.705104044768659.118679019 808918.47944432
768683.753640784808911.491154701768775.348126624808901.024570139
768826.246366707808879.352794821768877.817857865808846.510588805
#Sta/Elev= 30
 9810.75865.58949821.958862.41969842.147 858.8659845.579858.7883 9857.39856.8244
  9869.2856.46169881.011855.37469915.949850.01099927.252 844.8579938.556838.6895
9954.514826.40659971.022815.00499981.369810.96779991.376 809.48110001.38806.6143
10011.39808.660710021.39814.2845 10031.4820.380510041.64 827.46410051.87835.8525
10062.11 841.58210072.34 844.92110082.98853.917210114.87875.6474 10126.7884.3276
10138.18 892.06510156.56906.2226 10161.6909.844910173.72917.029810189.26926.9751
#Mann= 3 , 0 , 0
 9810.75    0.04       0 9810.75    0.04       010189.26    0.04       0
#XS Ineff= 2 , 0
       0                               0
Bank Sta=9810.75,10189.26
Exp/Cntr=0.3,0.1

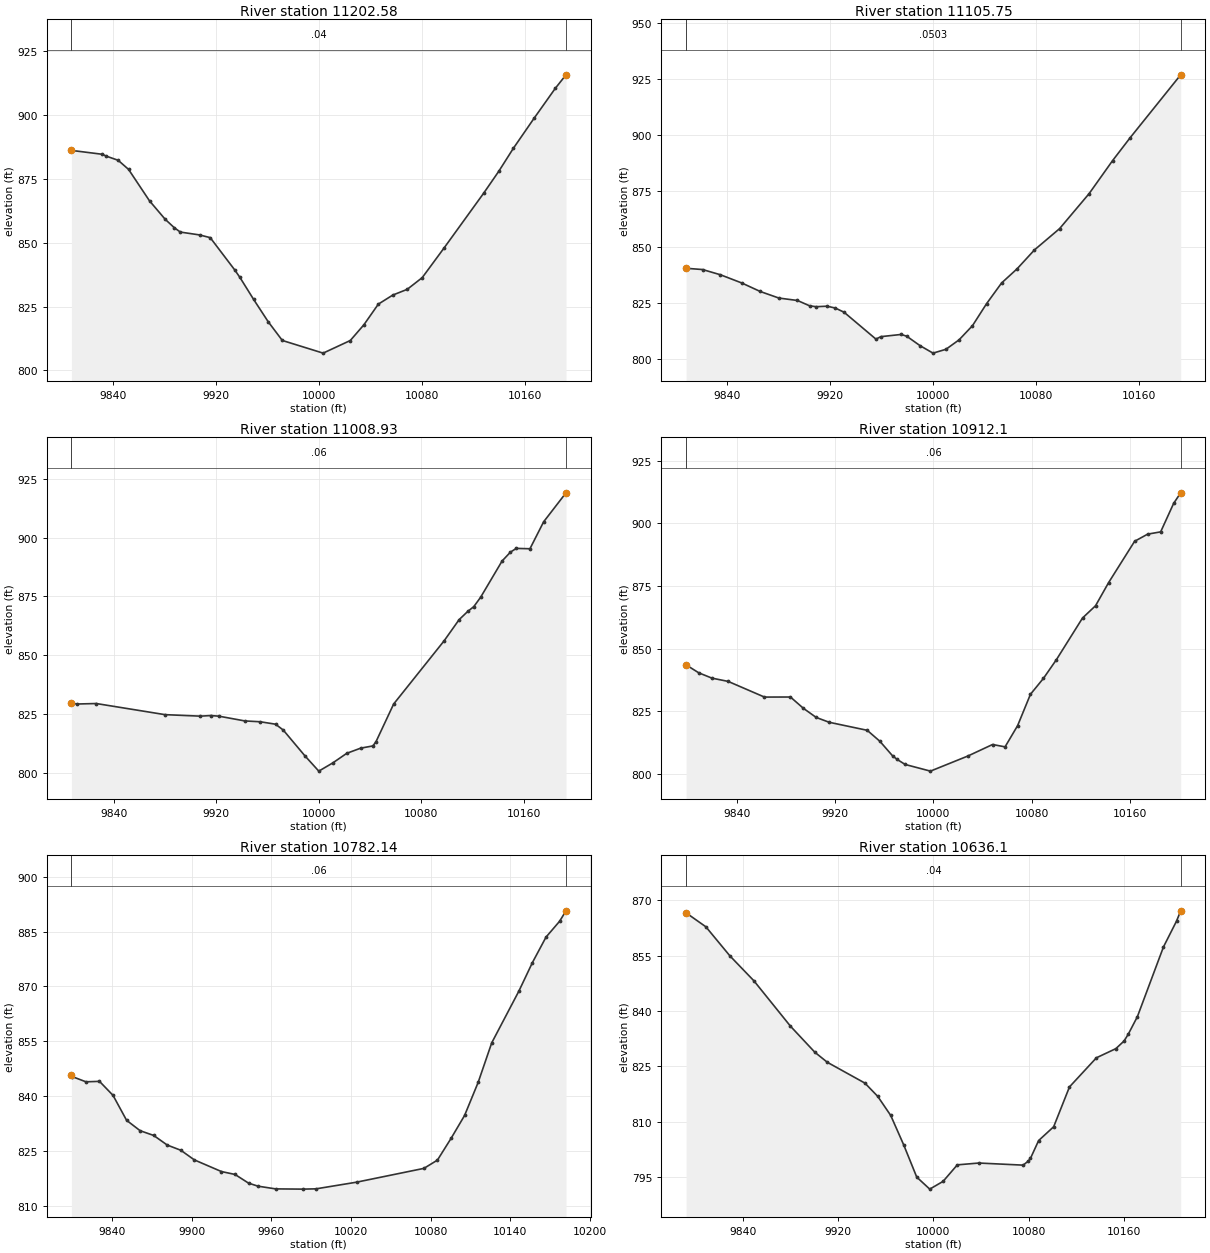
Type RM Length L Ch R = 1 ,11202.58,96.825200,96.825200,96.825200
XS GIS Cut Line= 6
768545.165420504 809100.36657568768651.349738162809031.095917749
768689.457660016809013.645424319768744.432284654808995.668454283
768778.548275518  808978.3156272768876.245326144808909.882816979
#Sta/Elev= 30
9807.837886.04689831.996884.5156 9834.75883.82999844.177882.17549852.264 878.614
9868.538866.30589880.719859.10139887.751855.82559892.467854.10539907.392852.9935
9915.704851.9284  9934.7839.33189938.715836.42269949.342827.84069960.712819.0723
9971.711811.728210003.43806.771910024.52811.7029 10035.1817.854510046.32825.9329
10057.54829.473710068.76831.712910080.42836.291710097.28 847.80910128.03869.2184
10139.93877.898110151.22886.8537 10167.5898.728410183.79910.290410192.13915.5922
#Mann= 3 , 0 , 0
9807.837    0.04       09807.837    0.04       010192.13    0.04       0
#XS Ineff= 2 , 0
       0                               0
Bank Sta=9807.837,10192.13
Exp/Cntr=0.3,0.1

Type RM Length L Ch R = 1 ,11105.75,96.825100,96.825100,96.825100
XS GIS Cut Line= 6
768665.111420689809214.250145277768767.421471947809102.906257293
768778.292796111809079.777380655768784.819718668809036.551196188
768803.355651448809004.052011664 768893.65306226808916.385707233
#Sta/Elev= 30
9807.871840.48399820.688839.92139834.543837.59749851.052833.9496  9865.5830.1323
9879.947827.20839894.394826.12089903.821823.75089908.842823.34959917.439823.5739
9923.823 822.7449930.595820.88869955.355808.89389959.173809.98969974.955810.9733
9979.283810.1833 9989.64805.96699999.718802.641310009.75804.347810019.94808.5632
10030.35814.875510041.33824.713610052.98833.929710065.05840.2628 10078.5848.6697
10098.04858.171710121.01873.813910139.15888.469710152.85898.718210192.11926.7727
#Mann= 3 , 0 , 0
9807.871  0.0503       09807.871  0.0503       010192.11  0.0503       0
#XS Ineff= 2 , 0
       0                               0
Bank Sta=9807.871,10192.11
Exp/Cntr=0.3,0.1

Type RM Length L Ch R = 1 ,11008.93,96.825200,96.825200,96.825200
XS GIS Cut Line= 6
768692.203733803809260.042896606768786.409223881809160.326873882
768869.572212503809117.739577425768891.919342312809100.310924156
768920.721164295809059.192047972768950.684300745808988.647852525
#Sta/Elev= 30
9806.731829.65359810.977829.26039826.162829.46529879.876824.74149907.504824.1013
9915.458824.35469921.896824.1055 9942.21822.07329954.326821.71619966.244820.6842
9972.263818.19469989.108807.289210000.03800.746810010.95804.235710021.88808.3151
 10032.8810.513710042.26811.450910044.68813.199110058.52829.265710097.91856.0842
10109.65865.093810116.46868.6243 10121.1870.614710126.44874.589910143.24890.0163
10149.76893.789610154.31895.372510165.01895.2217 10175.7906.669710193.17918.9818
#Mann= 3 , 0 , 0
9806.731    0.06       09806.731    0.06       010193.17    0.06       0
#XS Ineff= 2 , 0
       0                               0
Bank Sta=9806.731,10193.17
Exp/Cntr=0.3,0.1

Type RM Length L Ch R = 1 , 10912.1,129.964600,129.964600,129.964600
XS GIS Cut Line= 6
768842.959067374809384.668998294768883.559834993809269.310431734
768904.040328836809184.655112079768907.633494232809143.090695752
768912.234234947809120.819791972768954.498105261808999.619631038
#Sta/Elev= 30
9798.846843.51589809.176840.3373 9819.86 838.2289833.062836.91839862.593830.6648
9883.724830.69159894.219826.19589904.714822.52949915.209820.61549946.172817.4069
9956.452813.03169966.732807.24749970.526805.78039977.012803.78219997.572801.1216
10028.01807.146510048.09811.740710058.27810.806110068.48819.279210078.91831.7726
 10089.5838.137410100.09845.637210121.27862.215610131.86 867.10710142.45876.3097
10163.63892.823510174.22895.669310184.81896.5811 10195.4907.9739 10201.1912.1565
#Mann= 3 , 0 , 0
9798.846    0.06       09798.846    0.06       0 10201.1    0.06       0
#XS Ineff= 2 , 0
       0                               0
Bank Sta=9798.846,10201.1
Exp/Cntr=0.3,0.1

Type RM Length L Ch R = 1 ,10782.14,146.035400,146.035400,146.035400
XS GIS Cut Line= 4
768986.984253556809365.740872234769017.366198003809216.435316667
769039.067586899809094.039483339769019.102309108809000.289483339
#Sta/Elev= 30
9809.365845.74659810.121845.29449820.326843.88259830.531844.00769840.736840.1622
9850.941833.33679861.146830.48859871.351829.19049881.556 826.5589891.761825.1376
9901.966822.49429922.376 819.3019932.581818.51029942.786816.13099949.864815.2978
9963.188814.5526  9983.5814.48619993.656814.566310024.12816.3882 10074.9820.1733
10085.06822.438510095.28828.3616 10105.5834.662110115.73843.723210125.95854.5593
 10146.4868.729410156.62876.561510166.85883.522910177.07887.858210181.89 890.719
#Mann= 3 , 0 , 0
9809.365    0.06       09809.365    0.06       010181.89    0.06       0
#XS Ineff= 2 , 0
       0                               0
Bank Sta=9809.365,10181.89
Exp/Cntr=0.3,0.1

Type RM Length L Ch R = 1 , 10636.1,95.533500,95.533500,95.533500
XS GIS Cut Line= 6
769222.976724854809371.477574188769203.249362624809263.485002172
769166.646206328809169.205760249769094.926268451809084.475445871
769069.633203572809041.937105801 769051.50787678809001.808016307
#Sta/Elev= 30
9791.976866.56099808.626862.77839828.835854.90349849.044848.14319879.778 835.853
9900.289 828.7989910.775826.08289942.357820.44999953.144816.85839964.084 811.684
9975.024803.69119985.964794.98519996.904791.729610008.14793.837610020.09798.3044
 10038.2798.797110075.45798.226110079.71799.3105 10081.6800.058110088.48804.8896
10101.12808.624510114.42819.420710137.08827.304610153.41829.778210160.35831.8558
10163.91833.728410171.52838.433910193.47857.336610204.44864.318710207.94867.1068
#Mann= 3 , 0 , 0
9791.976    0.04       09791.976    0.04       010207.94    0.04       0
#XS Ineff= 2 , 0
       0                               0
Bank Sta=9791.976,10207.94
Exp/Cntr=0.3,0.1