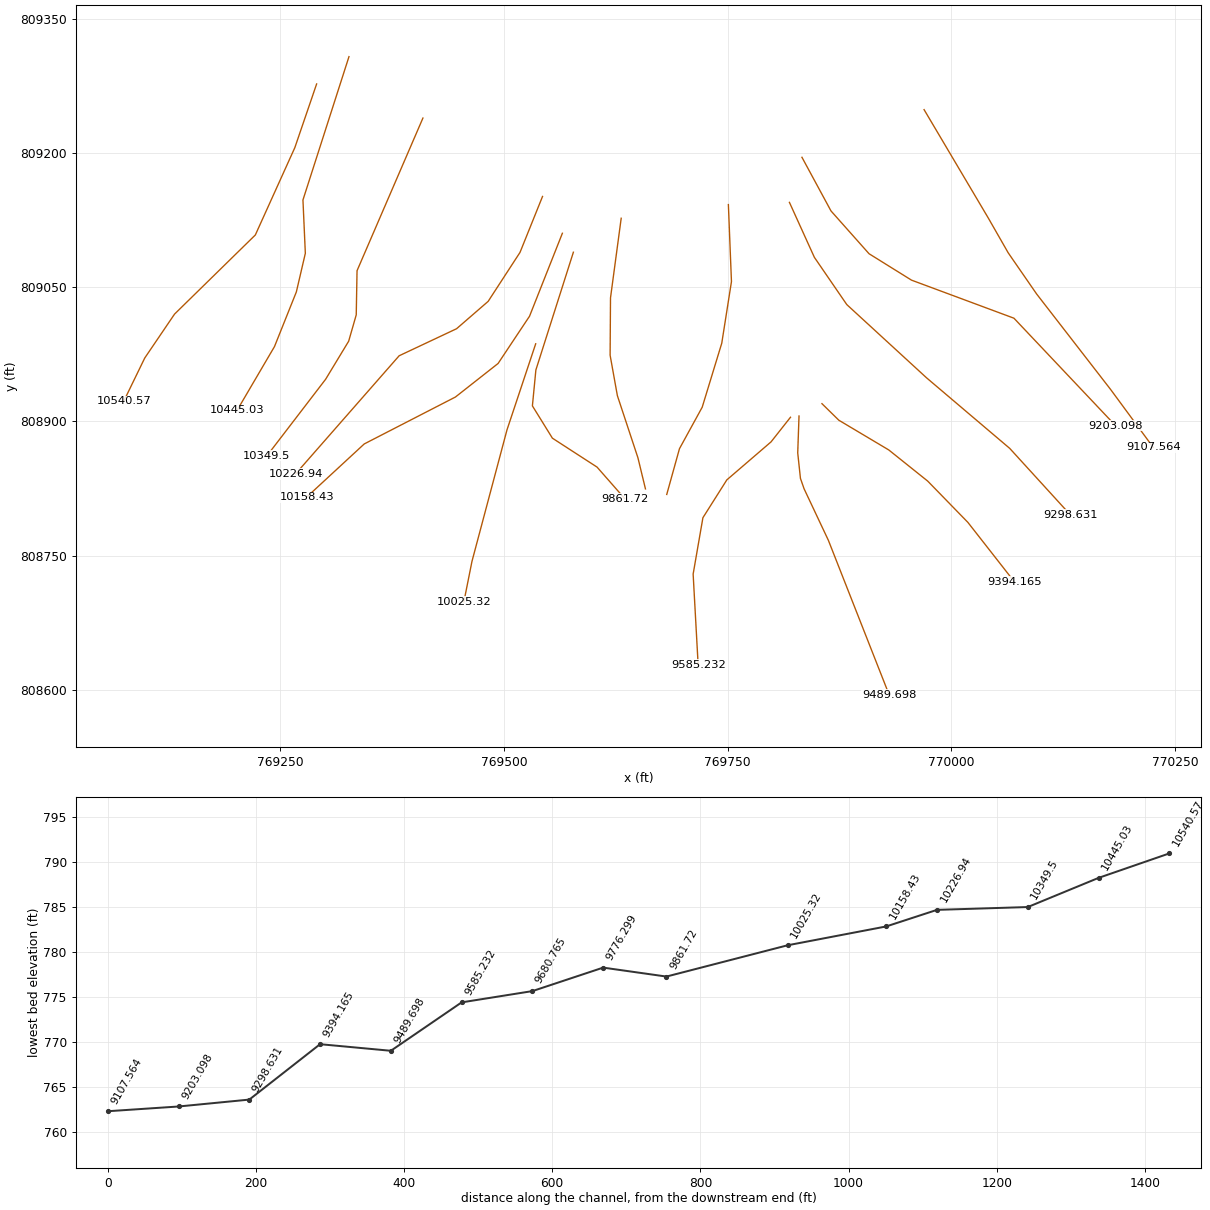
HEC-RAS study 17730_ras.prj: 17730

--- 17730_ras.g01 (geometry) --- (continued)

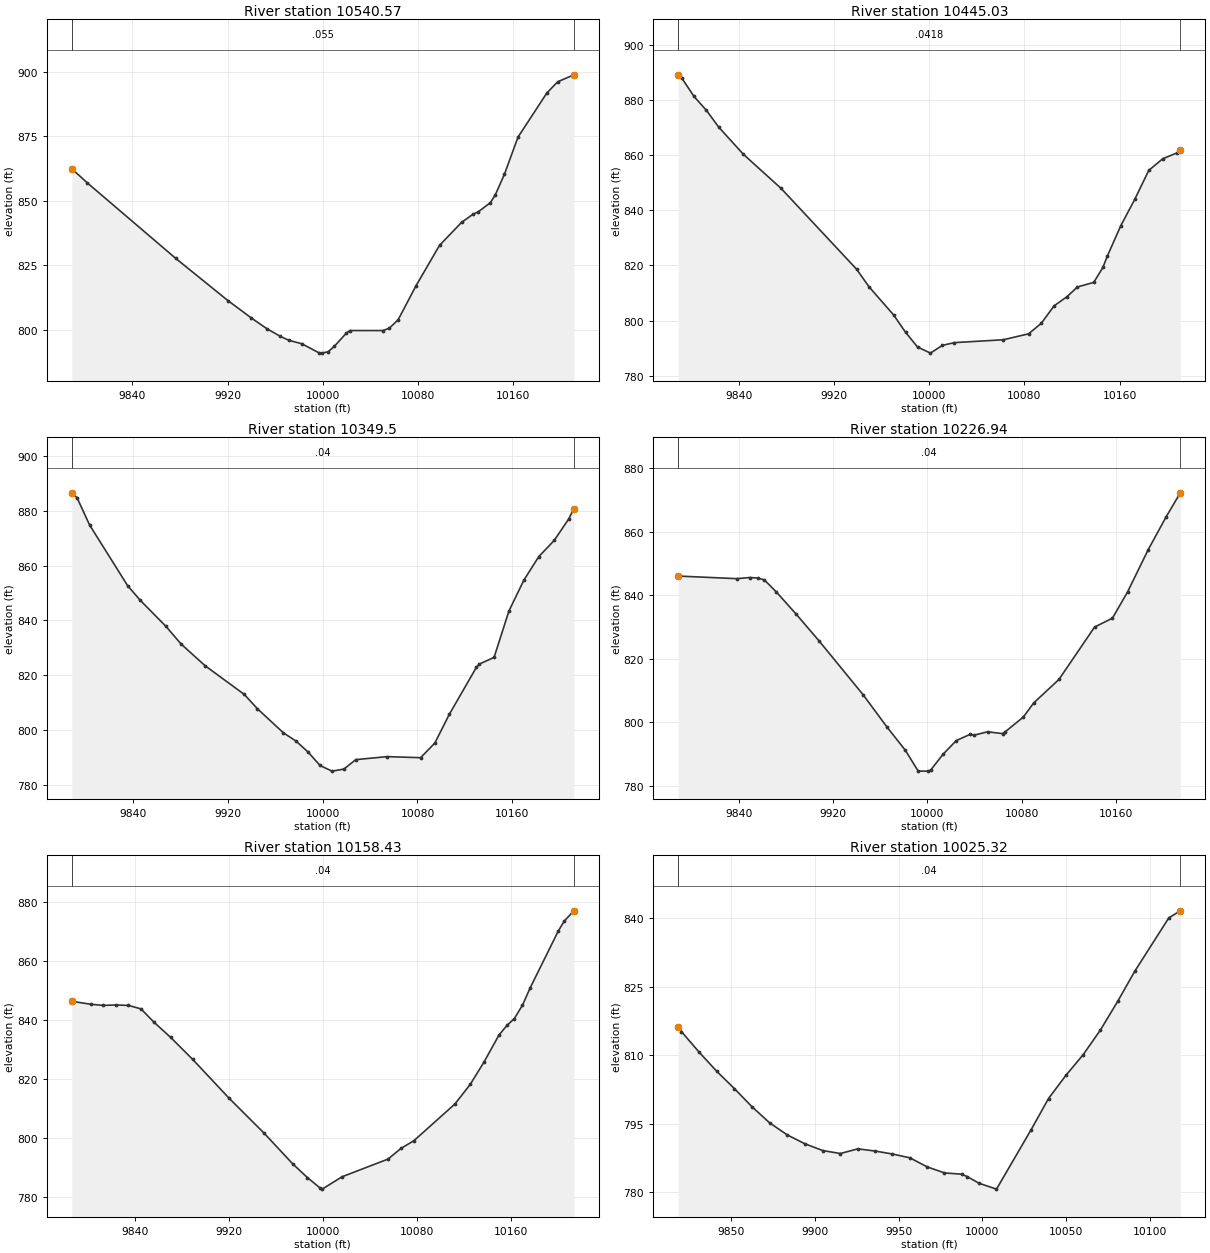
Type RM Length L Ch R = 1 ,10540.57,95.533500,95.533500,95.533500
XS GIS Cut Line= 6
769290.554966002809277.220572146769266.184445355809206.006138994
769222.065346056809108.460938776769131.757812569809020.000749141
769098.477760695808970.957511049769075.072147124808922.794686869
#Sta/Elev= 30
9789.022862.36619801.833856.99689876.399827.6307  9920.3 811.2699939.991804.5267
9953.226800.30859964.257797.43929971.378795.91069982.414794.54169996.486791.1141
    9999790.922810004.47791.428610009.62793.526410019.79798.691310022.83799.6761
10050.42799.666910055.82800.556610063.32803.865710078.29816.986610098.11832.7066
10116.69841.623810126.52844.834910130.27845.5492 10140.9849.260610145.05852.3444
10152.67860.281110164.05874.636710188.26891.7051 10197.4896.065310210.97898.7619
#Mann= 3 , 0 , 0
9789.022   0.055       09789.022   0.055       010210.97   0.055       0
#XS Ineff= 2 , 0
       0                               0
Bank Sta=9789.022,10210.97
Exp/Cntr=0.3,0.1

Type RM Length L Ch R = 1 ,10445.03,95.533600,95.533600,95.533600
XS GIS Cut Line= 6
769326.712246003809307.741949336769275.273597657809147.560399861
769277.940201251809087.933955977769267.886061814809044.736099497
769243.426466553 808983.64420041 769201.65309436808912.450480513
#Sta/Elev= 30
9789.097889.15919791.946888.07729802.333881.3344 9812.72876.29929823.108870.1896
9843.883860.31349875.498847.97279938.956818.65629949.532812.21099970.028802.0951
9980.082795.79419990.165790.436210001.04788.208610011.06791.024510021.12 792.019
10062.28793.058410083.51795.214610094.12799.016810105.01805.383410115.97808.7405
10124.57812.219410138.27813.872510145.96819.309610149.67823.419810161.07834.5025
10172.68843.965510184.45854.474510196.22858.725410207.99860.793410210.99861.8007
#Mann= 3 , 0 , 0
9789.097  0.0418       09789.097  0.0418       010210.99  0.0418       0
#XS Ineff= 2 , 0
       0                               0
Bank Sta=9789.097,10210.99
Exp/Cntr=0.3,0.1

Type RM Length L Ch R = 1 , 10349.5,122.562500,122.562500,122.562500
XS GIS Cut Line= 6
769409.363482332809239.119155931769335.722170605809068.494796336
 769334.82443873809019.155172628769326.358878976808989.692952139
769300.628670651808947.202321361 769234.93875647808861.522384133
#Sta/Elev= 30
9787.968886.52529792.375 884.7849803.072874.74969835.163852.6458 9845.86847.2912
9867.589837.77699880.332831.34159900.641 823.4219933.693 812.9689944.711807.7742
9966.745798.94799977.466795.92389987.634791.91569997.696787.030910007.78784.9741
 10017.8785.708110027.88789.170410054.39790.265610082.67789.879610094.72795.2584
 10106.9 805.71210129.81 822.877 10132.1824.0038 10144.7826.4799 10157.3 843.449
 10169.9854.683410182.51863.271810195.55869.178410207.71876.962410212.09880.7565
#Mann= 3 , 0 , 0
9787.968    0.04       09787.968    0.04       010212.09    0.04       0
#XS Ineff= 2 , 0
       0                               0
Bank Sta=9787.968,10212.09
Exp/Cntr=0.3,0.1

Type RM Length L Ch R = 1 ,10226.94,68.504500,68.504500,68.504500
XS GIS Cut Line= 6
769543.019239725809151.476800386 769517.87196499809088.997609226
769482.254351101809034.236958386769446.985861415809003.673440098
769382.765394445808973.430194619769266.980760275808841.356761511
#Sta/Elev= 30
9788.213846.09299838.011845.26639849.008845.62569855.609845.48239861.458844.8658
9871.677841.04869888.073834.25789907.654825.79629945.434 808.6829965.638798.5581
 9981.28791.21639992.185784.6663 10000.6784.661510002.68784.940710013.27789.9483
10024.47794.257610036.63796.303710039.35795.955110051.13797.047610063.86796.4823
 10066.3 797.09110081.46801.656510090.45806.1634 10111.8813.523210142.14830.0347
10157.31832.828810170.24841.156610187.65854.360810202.82864.659510214.99872.2985
#Mann= 3 , 0 , 0
9788.213    0.04       09788.213    0.04       010214.99    0.04       0
#XS Ineff= 2 , 0
       0                               0
Bank Sta=9788.213,10214.99
Exp/Cntr=0.3,0.1

Type RM Length L Ch R = 1 ,10158.43,133.109000,133.109000,133.109000
XS GIS Cut Line= 6
769565.212133614809110.367897894769528.511321869809017.670154495
769493.371387771808964.841904841769445.707173641808927.354655997
769343.785484792808874.913993534769279.342277442808815.381804893
#Sta/Elev= 30
9786.582846.36929802.909845.36979813.534844.98639824.158845.14269834.783844.9809
9845.429843.81939856.392839.33089870.521834.21099889.424826.69939920.085 813.677
 9949.98801.8019 9974.42791.36649986.935786.7198 9997.27783.33549999.448782.8237
10016.37787.005710055.45792.993310066.44 796.60810077.44799.2154 10112.4811.6765
10125.34818.285210136.87825.735110149.81  835.0110156.88838.379110162.75840.4948
10169.68845.044910176.38851.029810200.04870.071610205.23873.528610213.38876.9923
#Mann= 3 , 0 , 0
9786.582    0.04       09786.582    0.04       010213.38    0.04       0
#XS Ineff= 2 , 0
       0                               0
Bank Sta=9786.582,10213.38
Exp/Cntr=0.3,0.1

Type RM Length L Ch R = 1 ,10025.32,163.604300,163.604300,163.604300
XS GIS Cut Line= 4
769535.380120722808986.816119622769503.304910241 808890.63485837
769464.181638598808743.736572891769455.094371706808698.300238386
#Sta/Elev= 30
9818.462816.12199820.376 815.1689830.918810.67879841.459806.48939852.001802.7059
9862.542798.72229873.083795.20439883.625792.56679894.166790.63629904.708789.1675
9915.249788.51499925.682789.5398 9936.03789.05889946.379788.41019956.727787.5811
9967.076785.60479977.425784.27489987.773783.99979990.977783.46959998.122782.0055
10008.47780.734710029.17793.738310039.52800.533910049.86805.580410060.21810.1174
10070.56815.543910080.78821.747410090.98  828.3310111.37840.040510118.21841.5615
#Mann= 3 , 0 , 0
9818.462    0.04       09818.462    0.04       010118.21    0.04       0
#XS Ineff= 2 , 0
       0                               0
Bank Sta=9818.462,10118.21
Exp/Cntr=0.3,0.1

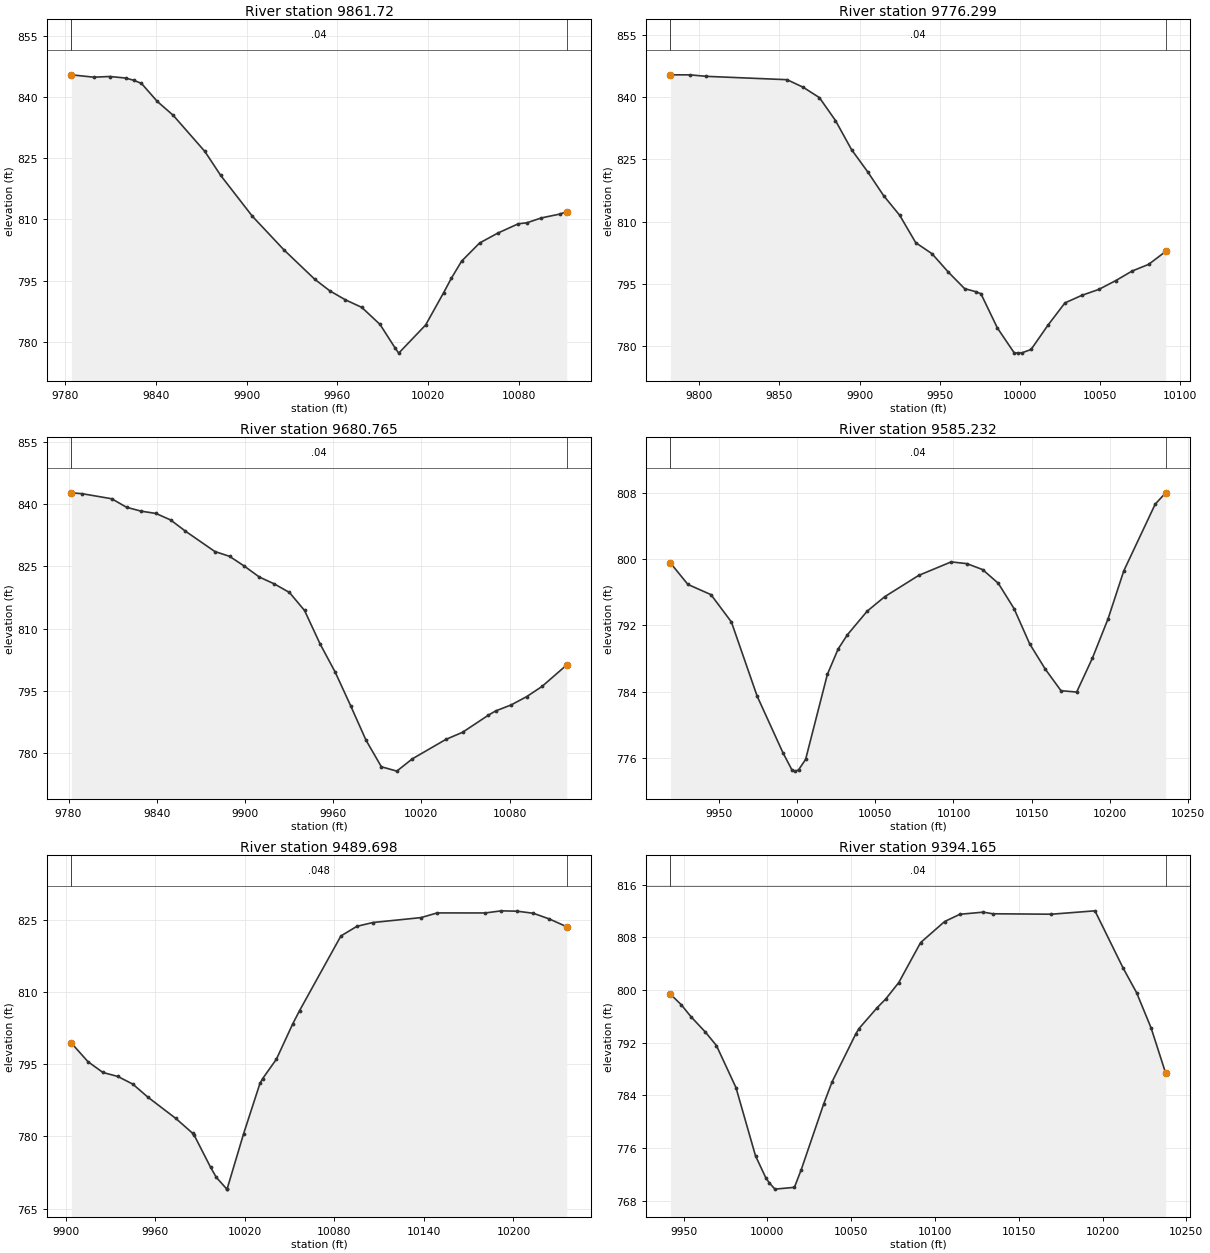
Type RM Length L Ch R = 1 , 9861.72,85.420800,85.420800,85.420800
XS GIS Cut Line= 6
769577.494861266809089.162859144769535.584941787808957.551963346
769531.703331409 808917.43633232769554.064001042808881.330828975
769603.965288483808849.010303756 769634.77603936808813.906717847
#Sta/Elev= 30
9783.981845.41499798.844 844.8359809.339 845.0059819.834844.6288 9825.16844.0864
9830.329843.31949840.824838.89769851.318835.51759872.308826.65799882.803820.7808
9903.792810.77249924.704802.54029945.088795.34449955.116792.50219965.337790.3232
9976.212788.46879988.308784.27849998.472778.406610000.66 777.26410018.47784.1534
10030.39792.061210035.48 795.586 10042.3799.790710054.22 804.238 10066.3806.6656
10079.83808.939310085.45809.179710095.14810.378210107.43 811.32410111.86811.9011
#Mann= 3 , 0 , 0
9783.981    0.04       09783.981    0.04       010111.86    0.04       0
#XS Ineff= 2 , 0
       0                               0
Bank Sta=9783.981,10111.86
Exp/Cntr=0.3,0.1

Type RM Length L Ch R = 1 ,9776.299,95.533500,95.533500,95.533500
XS GIS Cut Line= 6
769630.933119316809127.111828281769618.983032178809038.107717364
 769618.55361134808974.047117107769626.665013484808928.886290814
769649.625799856808859.471951573769658.048309054808824.647712387
#Sta/Elev= 30
9781.998845.40029794.218845.39529804.308 845.0389854.757844.22459864.846842.3888
9874.912839.89769884.922834.37589894.933827.35799904.944822.03679914.955816.2431
9924.967811.50869934.978804.89029945.124802.24049955.284797.80339965.444793.8142
9972.397793.08679975.604792.58969985.876784.32249996.325778.3419    9999778.2568
   10001778.306410006.86779.134210017.42785.012810027.98  790.3710038.54792.2048
 10049.1793.627110059.55795.730510069.86798.062210080.17  799.6710090.78802.7834
#Mann= 3 , 0 , 0
9781.998    0.04       09781.998    0.04       010090.78    0.04       0
#XS Ineff= 2 , 0
       0                               0
Bank Sta=9781.998,10090.78
Exp/Cntr=0.3,0.1

Type RM Length L Ch R = 1 ,9680.765,95.533500,95.533500,95.533500
XS GIS Cut Line= 6
769750.727821545809142.386802395769754.171693735809056.360863195
769743.334499089808987.500901988769721.483689717808915.970050969
769696.065756496808869.600867506769681.843642658 808818.45101093
#Sta/Elev= 30
9781.968842.7519 9789.37842.53759809.414 841.3199819.436839.27319829.458838.3262
9839.479837.77829849.483 836.2029859.484833.5176 9879.54828.60029889.588 827.434
9899.636825.06529909.837822.43919920.054820.78249930.272818.72469940.548814.3815
9950.999806.40289961.449799.4796  9971.9791.41799982.351783.11669992.801776.7056
10003.31775.651210013.84778.609510036.65783.294210048.05 785.01910065.61789.1481
10070.48790.154610081.06791.611710091.65 793.61610102.05796.061110118.86801.2434
#Mann= 3 , 0 , 0
9781.968    0.04       09781.968    0.04       010118.86    0.04       0
#XS Ineff= 2 , 0
       0                               0
Bank Sta=9781.968,10118.86
Exp/Cntr=0.3,0.1

Type RM Length L Ch R = 1 ,9585.232,95.533500,95.533500,95.533500
XS GIS Cut Line= 6
769820.129802554 808904.71672884769798.449153431808877.241856407
769748.999698821808834.734911755 769722.26398032808792.454817256
769711.342614546808729.450464528769716.914674329808628.350815531
#Sta/Elev= 30
9919.141799.53399930.326 796.9359945.058795.70399958.121792.40369974.559783.4534
9990.997776.64029996.912774.5047    9999774.4011   10001774.550410005.51775.8069
10019.43786.080910026.29789.138710032.16 790.84510044.83 793.70410056.02795.4499
10077.79798.028110098.51799.655710108.56799.4457 10118.6798.728610128.65797.0674
10138.68794.022710148.68789.760610158.68786.702910168.68784.109810178.69783.9459
10188.72788.031210198.76792.7913 10208.8798.579810228.87806.628510235.54807.9925
#Mann= 3 , 0 , 0
9919.141    0.04       09919.141    0.04       010235.54    0.04       0
#XS Ineff= 2 , 0
       0                               0
Bank Sta=9919.141,10235.54
Exp/Cntr=0.3,0.1

Type RM Length L Ch R = 1 ,9489.698,95.533600,95.533600,95.533600
XS GIS Cut Line= 6
769829.665636701808906.119057394769828.228149834808864.945492383
769831.266987668  808836.3904813769835.303516674808824.840862025
769862.513830096808767.116726471769930.507063714 808594.23919287
#Sta/Elev= 30
 9903.94799.37319915.065795.50139925.071793.27119935.078792.43879945.084790.8484
 9955.14788.14889973.854783.72429985.169780.63189986.089780.28579997.129773.5885
   10001771.474710008.04769.032310008.21769.049310019.22780.493710030.23791.0092
10031.95791.970610041.23796.029810052.19803.381510056.71806.104410084.43821.6366
10095.17823.645310105.92824.436410138.15825.4562 10148.9826.429610181.14826.4207
10191.88826.863210202.63826.782810213.37826.352610224.12825.164210235.68823.5637
#Mann= 3 , 0 , 0
 9903.94   0.048       0 9903.94   0.048       010235.68   0.048       0
#XS Ineff= 2 , 0
       0                               0
Bank Sta=9903.94,10235.68
Exp/Cntr=0.3,0.1

Type RM Length L Ch R = 1 ,9394.165,95.533500,95.533500,95.533500
XS GIS Cut Line= 6
769855.321911135808919.897063867769874.165559065808901.412339382
769930.007120292808868.162926302769973.508579395808833.357405876
770018.381452649808787.249363024770070.155506406808721.089452764
#Sta/Elev= 30
9942.093799.36039948.529797.76389954.461 795.9149962.999793.59329969.555791.5633
9981.221  785.189992.888774.8228    9999771.5039   10001770.750110004.48769.7634
10016.11770.0332 10020.2772.734510033.58782.687610038.64786.079510052.78793.3443
10054.64794.135910065.58797.326910070.65798.635410078.39801.119110091.43807.1879
10105.76810.3819 10114.9811.483210128.86 811.80510134.44811.558210169.53811.4926
10195.48 812.00510212.25 803.33810220.34799.574110229.02794.205410237.67787.3645
#Mann= 3 , 0 , 0
9942.093    0.04       09942.093    0.04       010237.67    0.04       0
#XS Ineff= 2 , 0
       0                               0
Bank Sta=9942.093,10237.67
Exp/Cntr=0.3,0.1

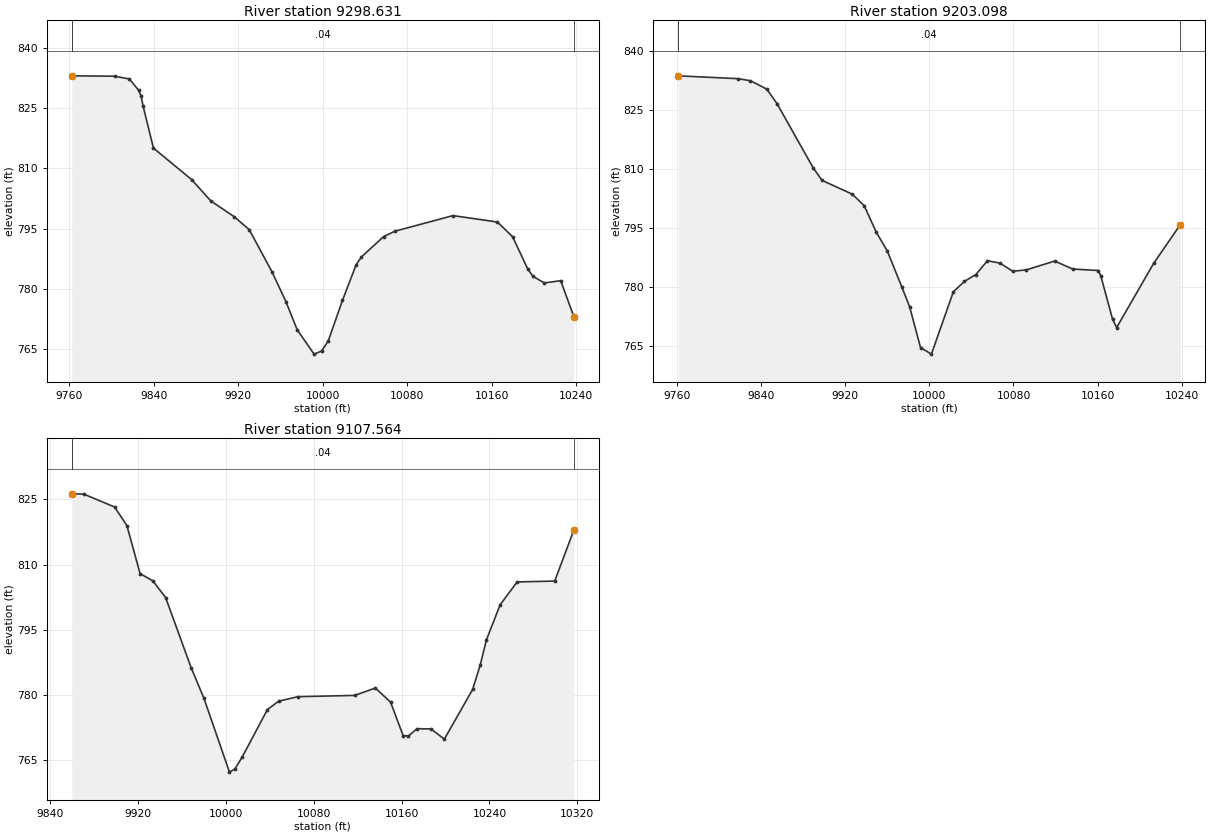
Type RM Length L Ch R = 1 ,9298.631,95.533500,95.533500,95.533500
XS GIS Cut Line= 6
 769818.95538112809144.870804559769846.827138406809083.459423554
769883.052564684809030.650580087769972.358819511808948.653121059
770065.140693909808869.948480958770133.070119095808795.489739337
#Sta/Elev= 30
9762.295833.14759802.995833.05119816.905 832.3589825.633829.51979828.052 828.009
9829.769825.66719839.629815.0953 9875.84 807.2099893.911 801.9019915.981797.9796
9930.295794.73879951.802784.23589965.116776.72639975.733769.71549991.745763.6187
    9999764.411510005.22766.960910018.63777.038310031.59785.947510036.65787.9101
10057.52792.966810068.08794.310510123.26798.225410165.36796.6214 10179.7792.9519
10194.35 784.76210199.05783.060810209.81781.399810225.27781.972210237.74772.9951
#Mann= 3 , 0 , 0
9762.295    0.04       09762.295    0.04       010237.74    0.04       0
#XS Ineff= 2 , 0
       0                               0
Bank Sta=9762.295,10237.74
Exp/Cntr=0.3,0.1

Type RM Length L Ch R = 1 ,9203.098,95.533500,95.533500,95.533500
XS GIS Cut Line= 6
769832.948728212809195.256705398769865.399611878809135.310805044
769907.903566083 809087.49594332 769955.35976784809057.966590996
770069.856893517809015.429074445770183.393933161808895.379807268
#Sta/Elev= 30
9761.582833.58149818.512832.8567 9830.21832.32949845.649830.20389855.363 826.534
9889.859810.15329898.169807.01419926.901803.49969938.237800.56459949.573793.9148
9960.266 788.9889973.841779.99979981.368774.87639991.713764.513710002.05762.8536
10022.89778.700310033.31781.322910044.25783.086210055.28786.583110067.04785.9961
10079.36783.911710092.23 784.26410119.12786.506610136.29784.482910160.66784.1017
   10163782.692510174.06771.765710178.02769.6118 10213.2 785.94710238.46795.7623
#Mann= 3 , 0 , 0
9761.582    0.04       09761.582    0.04       010238.46    0.04       0
#XS Ineff= 2 , 0
       0                               0
Bank Sta=9761.582,10238.46
Exp/Cntr=0.3,0.1

Type RM Length L Ch R = 1 ,9107.564,95.533500,95.533500,95.533500
XS GIS Cut Line= 6
769969.450615554809248.499097857770041.371065719809127.079005088
770063.511282508809088.394998266770095.275262789809042.409746408
770177.951085555808935.711199121770225.588826576808870.969161122
#Sta/Elev= 30
9859.878826.26319870.773826.19839898.804823.24419910.039818.98489922.045807.9335
9933.665806.26699945.286802.44129968.526786.31089980.146779.2996 10003.4762.3278
10008.31763.055710014.92765.771110037.96776.705310048.19778.632210065.79779.6593
10117.34 779.95410136.14781.643310149.99778.420810161.44770.726810166.32770.6271
10174.09772.299410186.74 772.25610198.97769.914510224.69781.316610231.62 786.948
10237.32792.759610249.74800.776710265.21806.0199 10299.4806.219310316.82817.9408
#Mann= 3 , 0 , 0
9859.878    0.04       09859.878    0.04       010316.82    0.04       0
#XS Ineff= 2 , 0
       0                               0
Bank Sta=9859.878,10316.82
Exp/Cntr=0.3,0.1