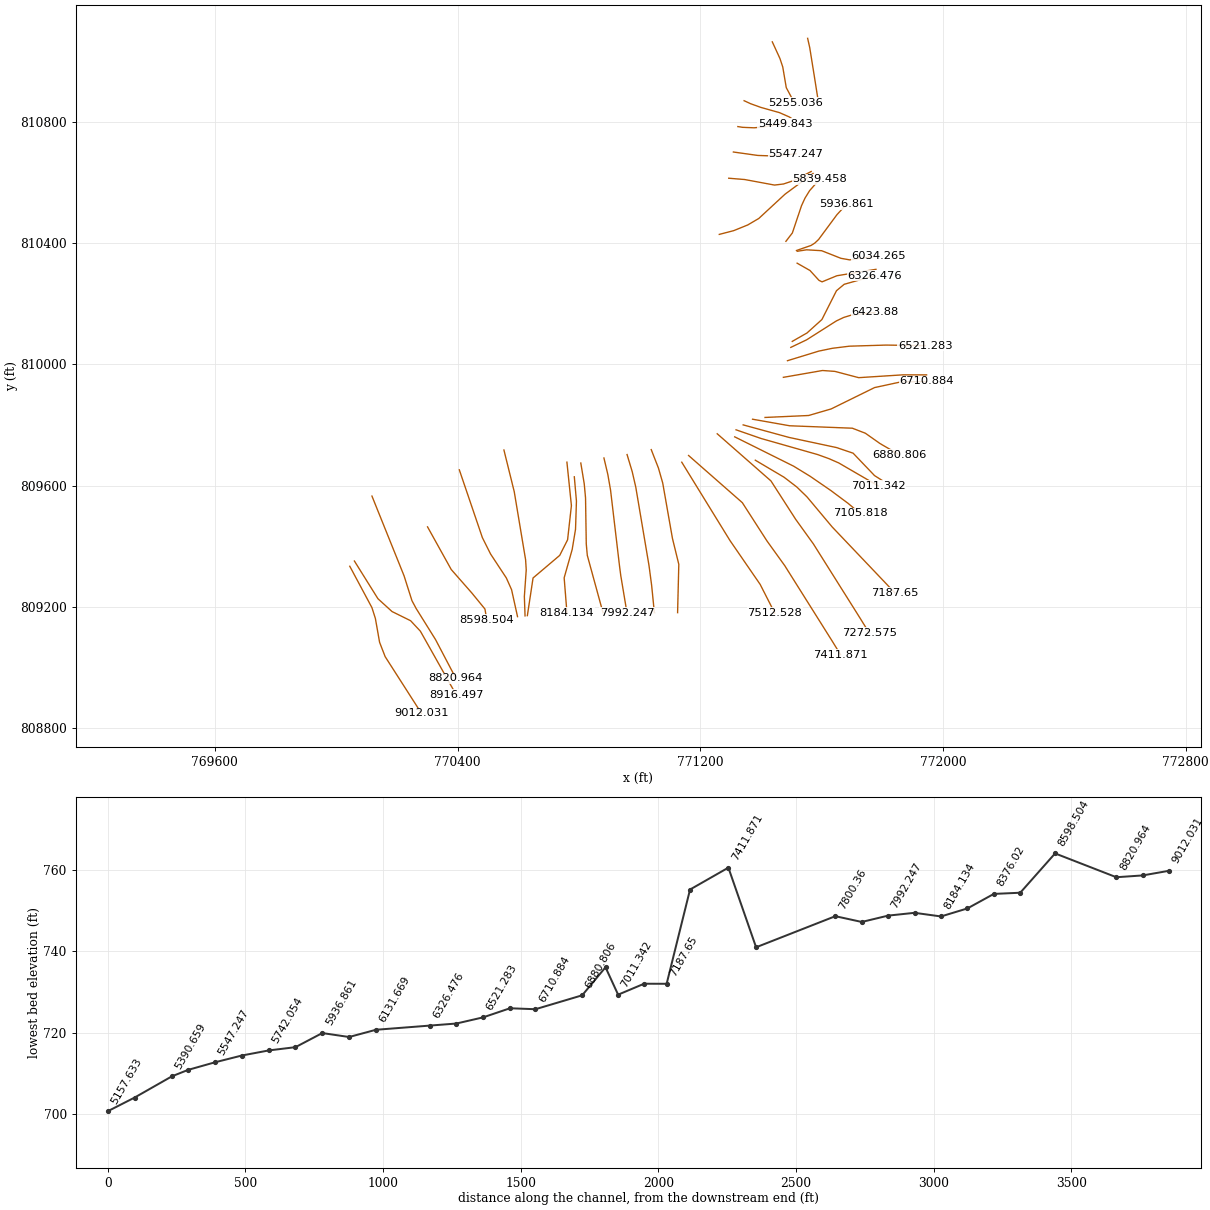
HEC-RAS study 17730_ras.prj: 17730

--- 17730_ras.g01 (geometry) --- (continued)

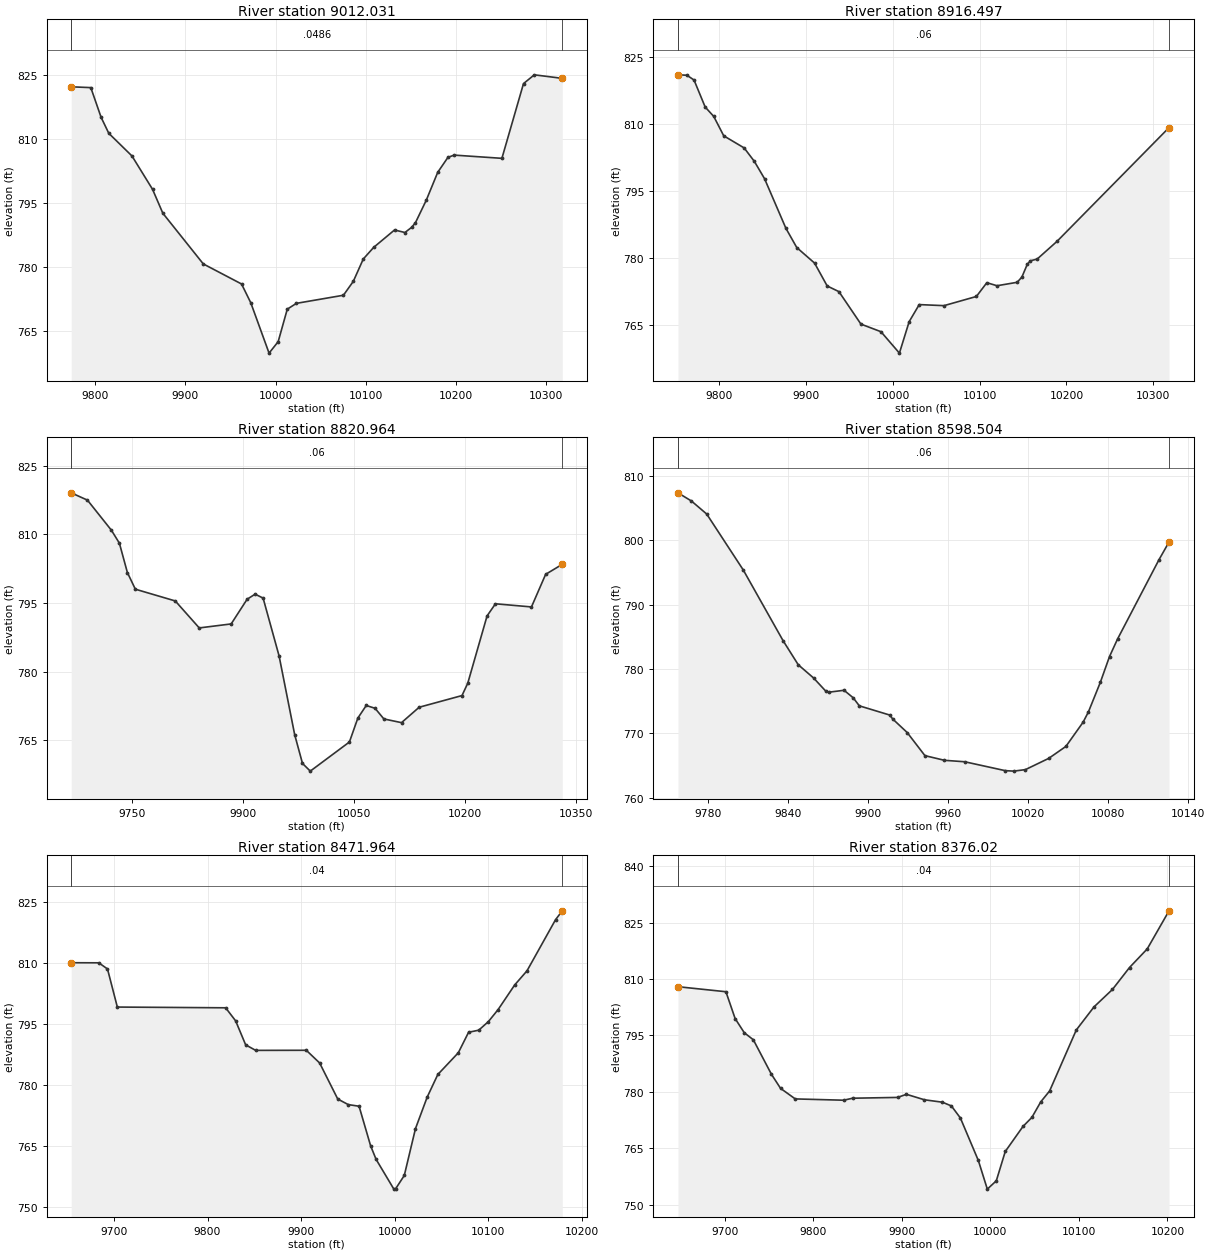
Type RM Length L Ch R = 1 ,9012.031,95.533600,95.533600,95.533600
XS GIS Cut Line= 6
770044.884728259809334.042937009770117.885556612809197.662107584
770129.323360627809161.855166882770143.162917214809083.255625546
770161.514081516809036.019227978770281.217108029808849.093888532
#Sta/Elev= 30
 9773.21822.29289794.952822.10259806.369815.13979814.892811.39099840.622806.0702
9863.457798.25059874.875792.64339919.776780.75159962.223776.04799972.475 771.639
9992.753 759.83310002.87762.524310012.97770.144610023.11771.507510075.28773.4083
10086.26776.673610097.29781.900210108.85784.635210131.98 788.71310143.54788.1215
10151.01789.342310155.25790.442510167.24795.708510179.91 802.23210191.21805.7322
10198.05806.275410251.14805.517210275.11823.0469 10287.1825.101710318.15824.2735
#Mann= 3 , 0 , 0
 9773.21  0.0486       0 9773.21  0.0486       010318.15  0.0486       0
#XS Ineff= 2 , 0
       0                               0
Bank Sta=9773.21,10318.15
Exp/Cntr=0.3,0.1

Type RM Length L Ch R = 1 ,8916.497,95.533500,95.533500,95.533500
XS GIS Cut Line= 6
770060.106046433809351.304225661770137.661144285809227.071579017
770184.083928075 809184.78692751770245.413697924809154.485692668
770277.627512487809119.960782044770395.254899905808911.105144741
#Sta/Elev= 30
9752.549821.01219762.846820.9213 9771.08819.84369783.887813.80149793.811811.6857
9805.263807.35539828.787804.64149840.549801.62729852.311797.73799876.892 786.638
9889.356782.34029909.899778.85029924.425773.72749937.941772.46189963.263765.1942
9986.348763.489110007.59758.692910018.83765.747710030.42769.560510058.94769.3256
10096.24771.380410108.26774.4643   10120 773.78310143.23 774.55410148.65775.7283
10154.85778.578710158.46779.364410166.27779.762210188.95783.6946 10318.1809.1935
#Mann= 3 , 0 , 0
9752.549    0.06       09752.549    0.06       0 10318.1    0.06       0
#XS Ineff= 2 , 0
       0                               0
Bank Sta=9752.549,10318.1
Exp/Cntr=0.3,0.1

Type RM Length L Ch R = 1 ,8820.964,222.459700,222.459700,222.459700
XS GIS Cut Line= 6
770117.978175905809565.327507777770223.685281874809302.852650422
770249.836367597809220.560751973770263.757726838809194.589224696
770327.383834166809092.623041617770394.348024837808965.098644905
#Sta/Elev= 30
9668.444819.03519690.358817.4373  9722.7810.8652 9733.48808.03879744.261801.6298
9755.041797.98669808.944795.41929841.285789.52819884.407790.40069905.968795.7987
9916.749796.90049927.529796.0427 9949.09783.41959970.186 766.1929980.706759.9317
9991.225758.251510044.08764.615410055.42769.827310066.77772.585610078.66771.9789
10090.58  769.6510114.41768.839510138.24772.204310196.06774.754410203.83777.4361
10229.94 792.15610241.24794.800110289.87794.113710309.01801.233110331.49803.4224
#Mann= 3 , 0 , 0
9668.444    0.06       09668.444    0.06       010331.49    0.06       0
#XS Ineff= 2 , 0
       0                               0
Bank Sta=9668.444,10331.49
Exp/Cntr=0.3,0.1

Type RM Length L Ch R = 1 ,8598.504,126.540300,126.540300,126.540300
XS GIS Cut Line= 5
 770301.22036469809463.831150025 770379.34536469809323.206150025
770447.921753556809245.081150025770490.456475765809192.997816667
770496.493721392809157.528998668
#Sta/Elev= 30
9757.573807.35629767.675806.08469779.115804.06169806.538795.35939836.313784.3943
9847.721780.63879859.192778.58629868.312 776.5479870.632776.37389882.071776.6699
9888.903775.50479893.511 774.253 9916.39772.81479918.442772.22359929.361770.1084
9942.667766.51379957.331765.7855 9972.49765.561710002.81764.1824 10009.2764.1057
10017.97764.338610035.41766.082910048.32767.945610061.23771.7129 10065.2 773.308
10074.14777.905910081.01781.914310087.06784.648410118.04796.943210125.62799.7154
#Mann= 3 , 0 , 0
9757.573    0.06       09757.573    0.06       010125.62    0.06       0
#XS Ineff= 2 , 0
       0                               0
Bank Sta=9757.573,10125.62
Exp/Cntr=0.3,0.1

Type RM Length L Ch R = 1 ,8471.964,95.943300,95.943300,95.943300
XS GIS Cut Line= 6
770405.931517588809651.855067921770481.988272157809428.257916886
770508.907146101809374.545677461 770561.00391091809295.352908193
  770578.2018206809256.779394904770597.831612899 809167.92262856
#Sta/Elev= 30
9654.447810.02659683.902810.00599693.184808.49479703.694799.14399819.365798.9616
 9830.05795.74719840.736789.86389851.421788.50889905.512 788.5319919.723 785.414
9939.069776.56599950.254775.19659961.837774.79459974.169765.08069980.012761.7572
    9999754.4413   10001754.574610010.12 757.78910022.08769.299510034.59777.0345
10045.94782.588110067.84787.927810078.79792.955810089.63793.464710099.99795.5822
10110.34798.532410128.03804.572910141.17808.040510171.67820.599410178.86822.7708
#Mann= 3 , 0 , 0
9654.447    0.04       09654.447    0.04       010178.86    0.04       0
#XS Ineff= 2 , 0
       0                               0
Bank Sta=9654.447,10178.86
Exp/Cntr=0.3,0.1

Type RM Length L Ch R = 1 , 8376.02,95.943400,95.943400,95.943400
XS GIS Cut Line= 6
770552.975002624 809717.24627479770586.968260773809579.887446136
770624.473214129809355.244665451770626.502557265809321.925904573
770620.321808373809234.286246473770622.649302099809170.468032578
#Sta/Elev= 30
9647.325807.96359701.483806.62799711.848799.50989722.185795.73189732.427793.8582
 9752.91784.66399763.151 780.9439779.753778.13379834.383777.78779844.522778.3197
9895.218778.53039905.357 779.3559925.636777.90169945.914 777.2599956.053776.2649
9966.193773.06529986.471761.7652 9996.61754.150710006.75756.359910016.87 764.157
10036.91770.824410046.92773.217210056.95777.350810066.97780.260410097.05 796.454
 10117.1 802.60810137.86807.226310157.15813.065810177.15818.011610201.77828.1366
#Mann= 3 , 0 , 0
9647.325    0.04       09647.325    0.04       010201.77    0.04       0
#XS Ineff= 2 , 0
       0                               0
Bank Sta=9647.325,10201.77
Exp/Cntr=0.3,0.1

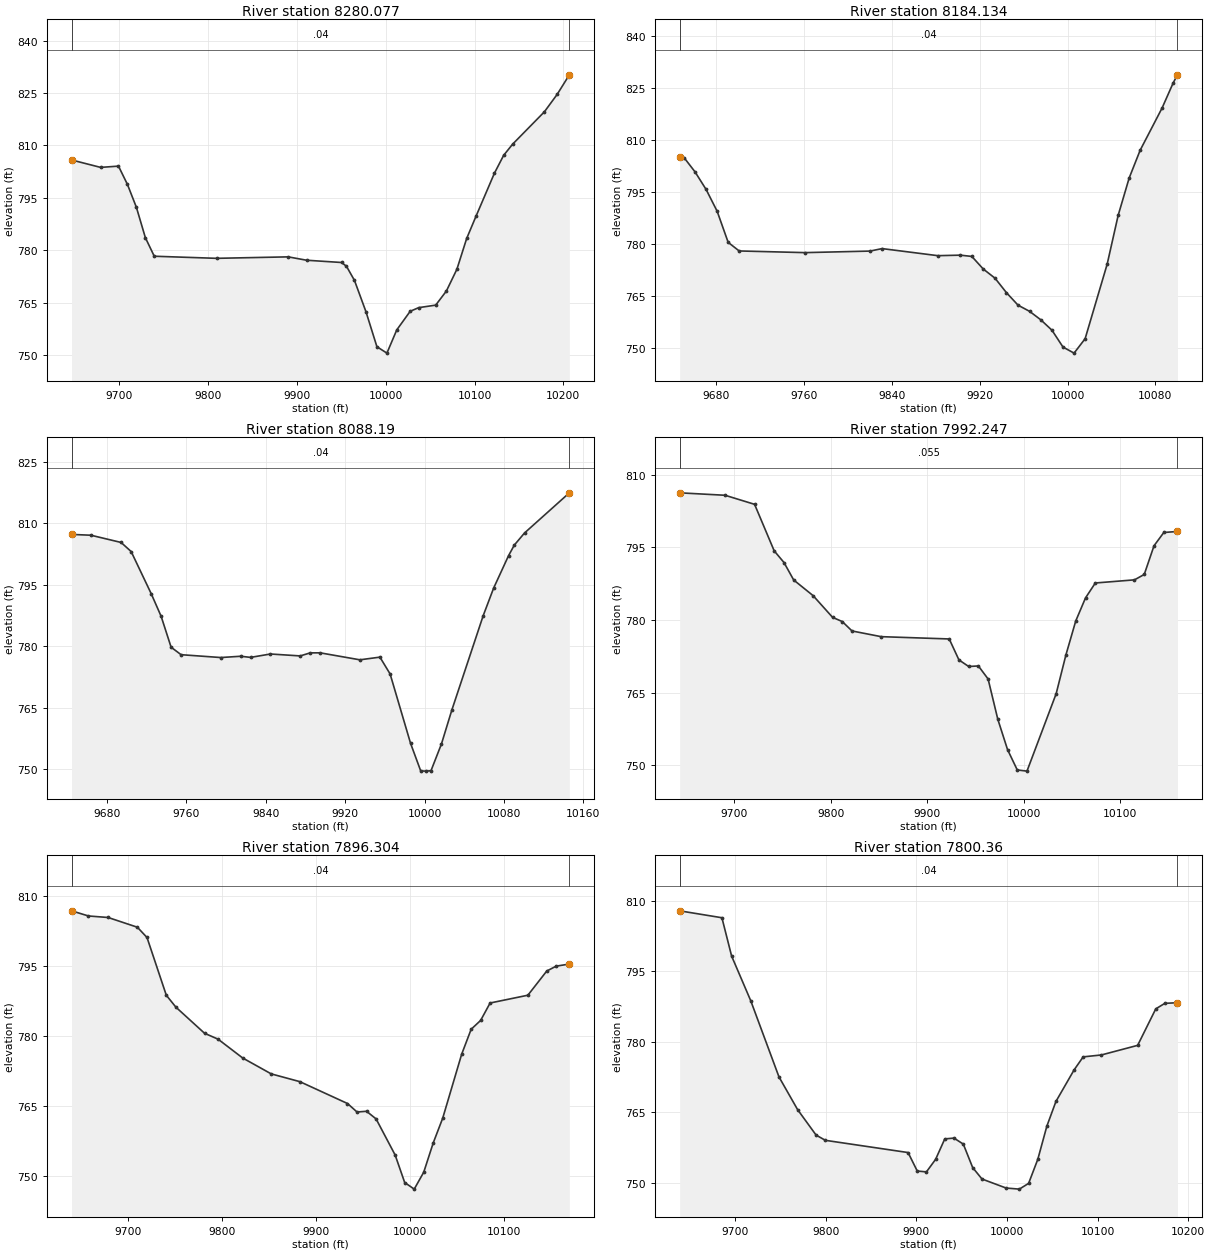
Type RM Length L Ch R = 1 ,8280.077,95.943300,95.943300,95.943300
XS GIS Cut Line= 6
770760.640547493809677.149248041 770775.42266585809534.032385487
770762.832806368 809421.21984832770736.898314236809369.892843914
770649.028387368809295.408304613770630.217266835809171.244234089
#Sta/Elev= 30
9646.633 805.8399679.282803.7127 9699.44804.07429709.519798.83439719.599792.2815
9729.671783.61499739.682778.29899809.763777.70019890.394778.11939911.136777.1536
9950.377776.50839955.955775.42639964.953 771.3829977.968762.36479990.197 752.421
10001.45750.584110012.55757.230710027.63762.548810037.19 763.59310056.35764.3154
 10068.4 768.36210080.22774.594510091.18783.373710101.76789.776910122.46802.0776
 10132.8807.161210142.84810.339810178.61819.605210192.97824.583610206.73830.1886
#Mann= 3 , 0 , 0
9646.633    0.04       09646.633    0.04       010206.73    0.04       0
#XS Ineff= 2 , 0
       0                               0
Bank Sta=9646.633,10206.73
Exp/Cntr=0.3,0.1

Type RM Length L Ch R = 1 ,8184.134,95.943300,95.943300,95.943300
XS GIS Cut Line= 6
770785.005521009809628.955824183 770792.01820381809548.634304763
770788.998924087809455.899792511770777.979052582809389.328724217
770751.527904764809295.962556309770760.662172107 809181.08683835
#Sta/Elev= 30
9646.546 805.1189650.529 804.9279660.597 800.7999670.666795.74359680.735789.4604
 9690.77780.50759700.788778.03469760.838777.5527 9820.04777.99839831.035778.7123
9881.771776.67599902.412776.82259912.783776.45549923.174772.83269933.916770.1852
9944.309766.02199954.876762.42159965.444760.63479975.683758.18659985.777755.2121
9995.832750.360310005.91748.612410015.99752.759810036.08774.2304 10046.1788.2937
10056.12799.039210066.13807.035210086.17819.233510096.18826.3911 10100.1828.7516
#Mann= 3 , 0 , 0
9646.546    0.04       09646.546    0.04       0 10100.1    0.04       0
#XS Ineff= 2 , 0
       0                               0
Bank Sta=9646.546,10100.1
Exp/Cntr=0.3,0.1

Type RM Length L Ch R = 1 , 8088.19,95.943300,95.943300,95.943300
XS GIS Cut Line= 6
770806.409955628809674.247341833770817.638600385809606.233958796
770821.991816336 809559.59545455770824.417301092809407.384545935
770827.833239963809369.813121607770879.520326453 809181.08683835
#Sta/Elev= 30
9644.342807.2952 9663.85807.10049694.256805.33329704.392 803.1169724.559792.8446
9734.603787.30599744.646779.7594 9754.69777.9319 9794.74777.23639814.756777.5501
9824.757777.27229844.757778.10039874.757777.63069884.757778.37299894.757778.3875
 9934.85776.68099955.045777.33419965.321 773.2279985.874756.3326 9996.15749.5561
   10001749.503410006.51 749.59510017.03756.120310027.56764.446410059.14787.4718
10069.66 794.20510084.63802.092610090.46804.6902 10100.8807.654410145.94817.4509
#Mann= 3 , 0 , 0
9644.342    0.04       09644.342    0.04       010145.94    0.04       0
#XS Ineff= 2 , 0
       0                               0
Bank Sta=9644.342,10145.94
Exp/Cntr=0.3,0.1

Type RM Length L Ch R = 1 ,7992.247,95.943400,95.943400,95.943400
XS GIS Cut Line= 6
 770882.65450392809690.830921596770895.406030101809636.835518131
770904.382808697809585.569316961770933.715987179809337.452050152
770937.988276313809304.234101571770958.511823018 809181.08683835
#Sta/Elev= 30
9643.628806.2584 9690.72805.75429721.276803.88499741.581794.28459751.728791.8754
9761.798788.26779781.937785.03259802.077780.55819812.146779.68569822.216777.7477
9852.425776.57179922.913776.09769932.982771.77249943.052770.41789953.122770.5271
9963.192767.83599973.261759.51359983.331753.26279993.401 749.06210003.47748.8186
10033.72764.809210043.85772.833710053.99779.809210064.13784.577110074.27787.6499
10114.82 788.29610124.96789.411410135.09795.337110145.23798.073810159.34798.2822
#Mann= 3 , 0 , 0
9643.628   0.055       09643.628   0.055       010159.34   0.055       0
#XS Ineff= 2 , 0
       0                               0
Bank Sta=9643.628,10159.34
Exp/Cntr=0.3,0.1

Type RM Length L Ch R = 1 ,7896.304,95.943300,95.943300,95.943300
XS GIS Cut Line= 6
770958.878425071809702.242749622770975.845606831809645.777593813
770987.548746001809595.064927152 771031.25465591 809335.97150772
771039.935098611809270.624276088771048.867559981 809181.08683835
#Sta/Elev= 30
9640.153806.90499658.158805.80069679.041805.47659710.174803.39069720.436801.1883
9740.962788.81389751.224786.24619781.646780.66399796.049779.39789822.209775.3668
9852.631771.95439883.053770.29299933.756 765.6079943.897763.78899954.037763.9423
9964.178762.3074 9984.46 754.566  9994.6748.677310004.75747.257510014.89750.8928
10024.98757.164910035.07762.470810055.24 776.17710065.33781.520610075.42783.4177
10085.49787.148910125.68788.817810145.78794.005210155.83795.048810169.82 795.497
#Mann= 3 , 0 , 0
9640.153    0.04       09640.153    0.04       010169.82    0.04       0
#XS Ineff= 2 , 0
       09944.832                       0
Bank Sta=9640.153,10169.82
Exp/Cntr=0.3,0.1

Type RM Length L Ch R = 1 , 7800.36,287.832100,287.832100,287.832100
XS GIS Cut Line= 6
771038.557643645809718.459328082771062.318799644809657.624422052
771076.400777404 809608.40261972771108.430187222809426.046367919
771129.415943733809340.337345668771125.429842758 809181.08683835
#Sta/Elev= 30
9638.704807.81569685.361806.34699696.097798.19029717.146788.72769748.349772.5217
9768.901765.56959789.329760.15679799.543759.04689890.827756.44959900.954752.5218
9911.081752.34039921.208755.00399931.336759.35229941.482759.5186 9951.79758.2424
9962.099753.26069972.408750.8236    9999748.909210013.61 748.67610023.87749.9001
   10034755.017810044.01762.070810054.02767.313510074.05774.012610084.07776.7796
10104.11777.185310144.19 779.22810164.19786.982510174.19788.1523 10188.1788.2919
#Mann= 3 , 0 , 0
9638.704    0.04       09638.704    0.04       0 10188.1    0.04       0
#XS Ineff= 2 , 0
       09948.698                       0
Bank Sta=9638.704,10188.1
Exp/Cntr=0.3,0.1

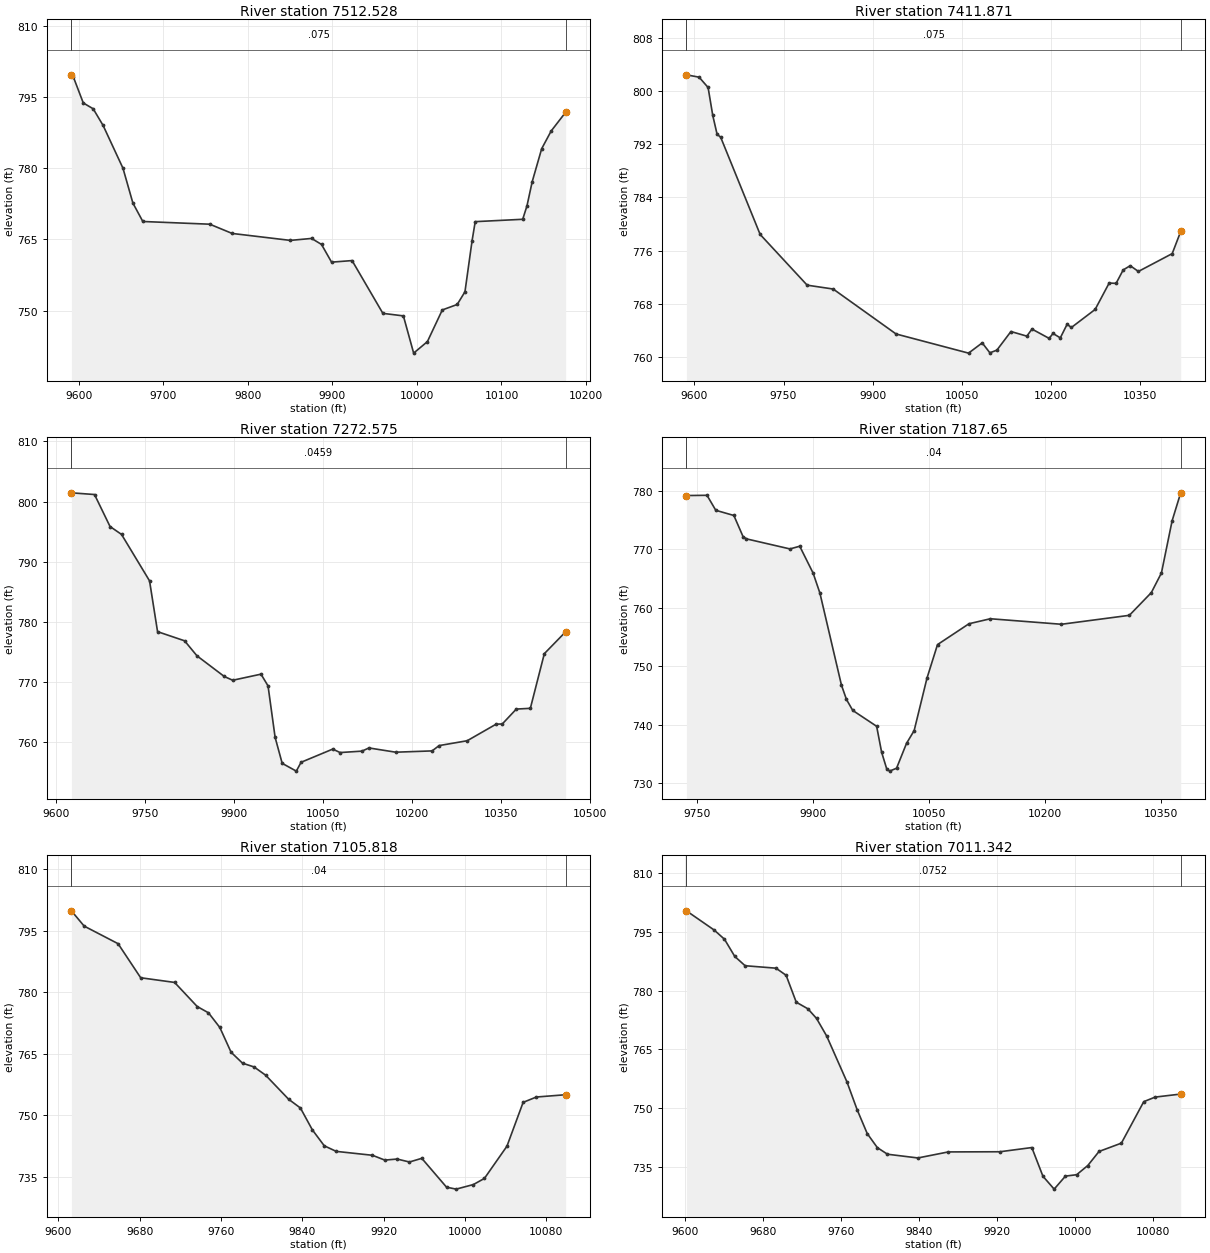
Type RM Length L Ch R = 1 ,7512.528,100.657400,100.657400,100.657400
XS GIS Cut Line= 4
771139.162614587809676.979166669 771298.22519547809418.631466922
771397.531560424809274.356182021771445.779464128809179.734079581
#Sta/Elev= 30
9591.167799.70649593.492 799.2629605.235793.77799616.978792.54379628.722789.0231
9652.209780.01049663.952772.66379675.695768.78469754.889 768.2149781.386766.2643
9850.257764.79869875.333765.21499887.077763.94849898.964760.21359923.244760.5444
9959.664749.41769983.944748.88249996.083741.032310012.33743.457210029.97750.1352
 10047.6751.288610056.78753.965410065.24764.777510068.92768.751710125.11  769.25
10130.17772.098610136.33777.177810147.56784.137210158.78787.867810175.92791.8202
#Mann= 3 , 0 , 0
9591.167   0.075       09591.167   0.075       010175.92   0.075       0
#XS Ineff= 2 , 0
       09914.331         10064.9       0
Bank Sta=9591.167,10175.92
Exp/Cntr=0.3,0.1

Type RM Length L Ch R = 1 ,7411.871,139.295800,139.295800,139.295800
XS GIS Cut Line= 6
771161.680434141809699.074205557771338.763767425 809543.69226111
771420.360989663 809416.95615002771478.520711872809336.226983334
771633.034600768809090.567261125771662.548489693809042.824205557
#Sta/Elev= 30
9586.453802.43369607.792802.08099622.954800.5305 9630.78796.34189638.116793.4876
9644.084793.06399710.603778.44299789.735770.82259833.561770.2409 9939.42763.4869
10061.46760.609310084.44762.150110097.35760.655410109.16761.060110132.79 763.856
10159.57763.162510168.23764.224910197.13762.824710203.67763.563310215.92762.9037
 10227.3764.9299 10234.7  764.4710274.55767.173110298.18771.142810309.83771.0919
10321.81773.115110333.62773.747210347.39772.8859 10404.3775.564410418.61778.8891
#Mann= 3 , 0 , 0
9586.453   0.075       09586.453   0.075       010418.61   0.075       0
#XS Ineff= 2 , 0
       0 9914.63        10065.79       0
Bank Sta=9586.453,10418.61
Exp/Cntr=0.3,0.1

Type RM Length L Ch R = 1 ,7272.575,84.925500,84.925500,84.925500
XS GIS Cut Line= 6
771256.081475807809770.688788891771433.164809091809615.306844443
 771514.76203133809488.570733353771572.921753539809407.841566667
771727.435642434809162.181844458 771756.94953136809114.438788891
#Sta/Elev= 30
9626.316801.44299665.265 801.1619691.396795.85069710.751794.53549757.915786.8245
9771.398778.38829816.884776.86919837.738774.37649883.767770.9415 9897.95770.3164
9945.523771.32959957.416769.3755 9969.31760.83969981.203756.521210004.99755.2262
10013.04756.695310066.34758.884710078.66758.312410115.49 758.546 10127.3759.0757
10172.38  758.3710233.63 758.58510245.44759.467510292.69760.272310341.42 763.027
10351.76763.056610375.39765.531210399.02765.654910422.55774.732510458.48778.3693
#Mann= 3 , 0 , 0
9626.316  0.0459       09626.316  0.0459       010458.48  0.0459       0
#XS Ineff= 2 , 0
       09951.479         10103.3       0
Bank Sta=9626.316,10458.48
Exp/Cntr=0.3,0.1

Type RM Length L Ch R = 1 , 7187.65,81.832000,81.832000,81.832000
XS GIS Cut Line= 6
771381.553446377809683.624246624771476.370821724809627.484581815
771518.449133462809595.233422096771551.702303133809563.001872859
771635.064526148 809463.46856461771841.170096076 809246.97597203
#Sta/Elev= 30
9736.877779.1387 9763.47779.18099774.812776.61959798.164775.73349810.002772.1304
9814.413771.73849870.611 770.0199883.211770.48189900.491765.89379909.279762.4824
9937.132 746.7439943.595744.30049951.694742.43099982.555739.72159988.984735.2915
9995.452732.49429999.262732.062110008.29732.559810021.12736.798710031.01738.9921
10047.55747.941710061.16753.675810101.83757.240110129.44758.091810221.26757.1491
10308.93758.677310337.29762.555710350.35765.911210364.16 774.83310375.24779.6034
#Mann= 3 , 0 , 0
9736.877    0.04       09736.877    0.04       010375.24    0.04       0
#XS Ineff= 2 , 0
       09920.497        10072.61       0
Bank Sta=9736.877,10375.24
Exp/Cntr=0.3,0.1

Type RM Length L Ch R = 1 ,7105.818,94.475100,94.475100,94.475100
XS GIS Cut Line= 6
771313.679130793809760.618597491771507.885850397809663.919632124
771562.598995451809630.402891997771630.366549309809583.818262017
771687.552763623809541.259279083771727.091343514809508.113708058
#Sta/Elev= 30
9612.748799.78829625.335796.0716 9658.69791.79259680.927783.50359714.282782.3678
9736.519776.50959747.637774.97099758.756771.41829769.874765.37749781.132762.7171
9792.463761.80579803.794759.80829826.456753.95039838.069751.81689849.796 746.504
9861.523742.62139873.251741.26499908.938740.31139921.072739.14189933.207 739.395
9945.342738.67899957.477739.57169981.819 732.5489991.289 732.07710008.22 733.191
10019.07734.679810041.24742.519110057.16753.186410070.18754.486710099.01755.0446
#Mann= 3 , 0 , 0
9612.748    0.04       09612.748    0.04       010099.01    0.04       0
#XS Ineff= 2 , 0
       0                               0
Bank Sta=9612.748,10099.01
Exp/Cntr=0.3,0.1

Type RM Length L Ch R = 1 ,7011.342,45.760200,45.760200,45.760200
XS GIS Cut Line= 6
771318.121206721809783.779429372771399.902878897809755.402950167
771587.248409306809702.133365946771624.710621593809688.573686962
771656.585770849809674.577196644771787.112145789 809598.80207353
#Sta/Elev= 30
9601.804800.30839630.255795.4155 9640.84793.07159651.425788.6775 9662.01786.3182
9693.668 785.6939704.065783.88089714.461777.02349726.406775.34049735.254772.8933
 9745.65768.40979766.443756.72379776.839749.66939787.236743.55419797.632  739.96
9808.029738.28099839.218737.32889870.407738.86879923.298738.90979956.062739.9833
 9967.47 732.669 9978.97729.38649990.553732.704710002.03733.0569 10013.5735.4069
10024.98 738.98210047.93741.106510070.88751.679910082.61752.842910108.76753.6145
#Mann= 3 , 0 , 0
9601.804  0.0752       09601.804  0.0752       010108.76  0.0752       0
#XS Ineff= 2 , 0
       09915.303                       0
Bank Sta=9601.804,10108.76
Exp/Cntr=0.3,0.1

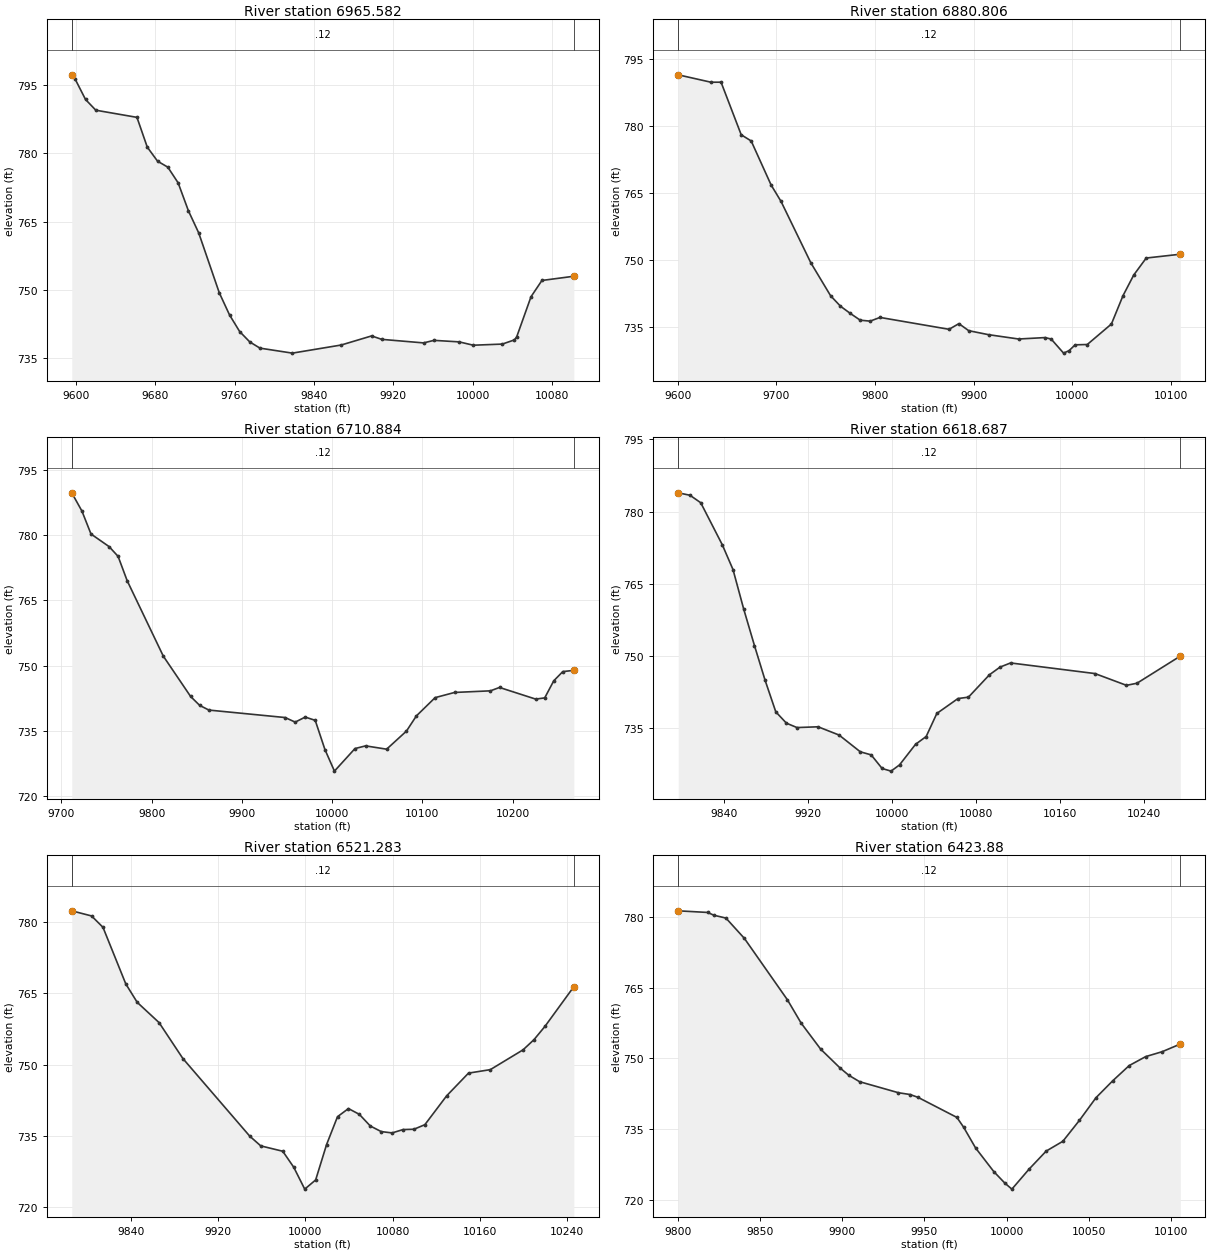
Type RM Length L Ch R = 1 ,6965.582,84.776600,84.776600,84.776600
XS GIS Cut Line= 6
  771341.6340473809800.010449484771492.458700091809758.777810588
771649.793769509809725.140657812771704.047241747 809706.69447726
771774.576755643809632.909755021771799.275928915809617.180928305
#Sta/Elev= 30
9596.022797.21529599.512796.23369609.879 791.8089620.246789.44849661.713787.8769
 9672.08781.35169682.447778.26139692.814776.94179703.181773.51119713.548767.3703
9723.915762.52039744.649749.3724 9754.98744.50799765.206740.85399775.432738.5706
9785.658737.21439818.282736.11899867.466737.89739898.144739.8967 9908.37739.1427
9950.458738.3642 9961.02738.92159986.427738.588710000.59737.856710029.84738.1035
10042.09739.028210044.32739.675910058.79748.507210069.76752.070410101.93752.9981
#Mann= 3 , 0 , 0
9596.022    0.12       09596.022    0.12       010101.93    0.12       0
#XS Ineff= 2 , 0
       09901.523                       0
Bank Sta=9596.022,10101.93
Exp/Cntr=0.3,0.1

Type RM Length L Ch R = 1 ,6880.806,169.921900,169.921900,169.921900
XS GIS Cut Line= 6
771372.514417382809818.719587712771494.593424267 809797.12725806
771701.417196474809789.072433862771744.363587402809772.539292117
771792.838944133809738.397270316771855.493235981809702.122406873
#Sta/Elev= 30
 9600.41 791.4699633.611789.81549643.832789.82429664.272778.06529674.403776.6738
9694.591766.83319704.685763.14989734.894749.42439754.941742.05989764.965739.7195
9774.989738.09879785.013 736.595 9795.03736.3871 9805.03737.21529875.034734.5598
9885.035735.82099895.035734.24889915.061733.35999945.572732.3891 9972.34732.7073
9978.615732.38069991.184729.23149996.746729.782910002.95 731.08910015.23731.1582
10039.69735.736310051.49742.092210062.37746.707510075.02 750.49810109.58751.3495
#Mann= 3 , 0 , 0
 9600.41    0.12       0 9600.41    0.12       010109.58    0.12       0
#XS Ineff= 2 , 0
       09867.306                       0
Bank Sta=9600.41,10109.58
Exp/Cntr=0.3,0.1

Type RM Length L Ch R = 1 ,6710.884,92.196800,92.196800,92.196800
XS GIS Cut Line= 6
771413.737511357809824.514553195771557.376650835809830.976866666
771631.663441554809852.619477707771774.661541818809922.962695859
771859.898150573809941.399200351771947.243821151809943.066729323
#Sta/Elev= 30
9711.569789.71779722.849785.51999732.866780.26089752.888 777.3749762.893775.1244
9772.898769.56039812.961752.22379843.213  742.969853.297740.90289863.511739.8301
9947.987738.11619959.081737.06489970.175738.22019981.269737.47519992.041730.7708
10002.57725.810510025.33730.993110037.12731.6102 10060.4730.850210082.38735.0096
10093.34 738.48610114.11 742.68710135.65743.876510175.39744.250110185.46745.0243
10225.51742.349810235.52742.628310245.54746.548810255.55748.6674 10267.8 748.952
#Mann= 3 , 0 , 0
9711.569    0.12       09711.569    0.12       0 10267.8    0.12       0
#XS Ineff= 2 , 0
       09938.286                       0
Bank Sta=9711.569,10267.8
Exp/Cntr=0.3,0.1

Type RM Length L Ch R = 1 ,6618.687,97.403600,97.403600,97.403600
XS GIS Cut Line= 6
771474.063236132809956.775974171771603.177156437809979.270473479
771644.059144867 809976.33723278771722.334067847809955.674822785
771867.683735109 809964.95907828771946.185690116809964.833996351
#Sta/Elev= 30
9796.477783.88399807.665783.38039817.895781.82139838.355 773.1089848.585767.9467
9858.814759.69559869.044752.1193  9879.2744.88789889.314738.36849899.429736.0161
9909.496735.10239929.545735.2645 9949.55733.54649969.741730.0644 9980.06729.4276
9990.506726.5962    9999726.049610007.05727.3432 10022.3731.622310032.42733.2452
10042.55738.032610062.65741.129810072.65741.423310092.65746.080210102.69 747.667
10112.73 748.53210193.02746.325510223.03743.877310233.03744.317810274.25749.9568
#Mann= 3 , 0 , 0
9796.477    0.12       09796.477    0.12       010274.25    0.12       0
#XS Ineff= 2 , 0
       0                               0
Bank Sta=9796.477,10274.25
Exp/Cntr=0.3,0.1

Type RM Length L Ch R = 1 ,6521.283,97.403700,97.403700,97.403700
XS GIS Cut Line= 6
771487.650645733810011.586202665771591.086610375810043.247142148
771635.587444158 810052.48797927771691.928940881810059.448234079
771812.478006284 810063.09334305771941.497984446810061.266798837
#Sta/Elev= 30
9786.052782.32789804.196781.25149814.654778.8576 9835.57766.95529846.028763.0868
9866.048758.8286 9887.86751.2781 9949.16  734.959959.236732.90869979.388 731.782
9989.464728.41559999.526723.817410009.54725.748910019.56733.197310029.57739.0473
10039.59740.7524 10049.6739.5358 10059.6737.0912 10069.6735.9161 10079.6735.6361
 10089.6736.3376 10099.6736.4064 10109.6737.3635 10129.6743.4401 10149.6 748.206
 10169.6 748.939 10199.6753.103110209.61755.241110219.62758.021910246.13 766.382
#Mann= 3 , 0 , 0
9786.052    0.12       09786.052    0.12       010246.13    0.12       0
#XS Ineff= 2 , 0
       0                               0
Bank Sta=9786.052,10246.13
Exp/Cntr=0.3,0.1

Type RM Length L Ch R = 1 , 6423.88,97.403600,97.403600,97.403600
XS GIS Cut Line= 6
771498.525258029810055.453282723 771550.74824545810080.414106795
771648.438302499810142.476647467771672.945313357810154.183338141
771696.830852299810161.484990827771775.983525611 810170.68764387
#Sta/Elev= 30
9800.192781.28569818.118780.94219821.878780.3489 9829.22779.74889840.437775.4471
9866.654762.41199874.987757.48539886.834751.97929898.681747.96859903.951746.4376
9910.529745.06999934.224742.72579941.248742.35029946.071741.75659969.766737.4961
9973.839735.4262 9981.12731.02969992.217726.0119    9999723.550810003.22722.2956
10013.69726.538210024.09730.356510034.25732.440210044.35736.885910054.45 741.696
10064.55745.2471 10074.6748.482910084.64750.385210094.68 751.42610105.71753.0488
#Mann= 3 , 0 , 0
9800.192    0.12       09800.192    0.12       010105.71    0.12       0
#XS Ineff= 2 , 0
       0                               0
Bank Sta=9800.192,10105.71
Exp/Cntr=0.3,0.1

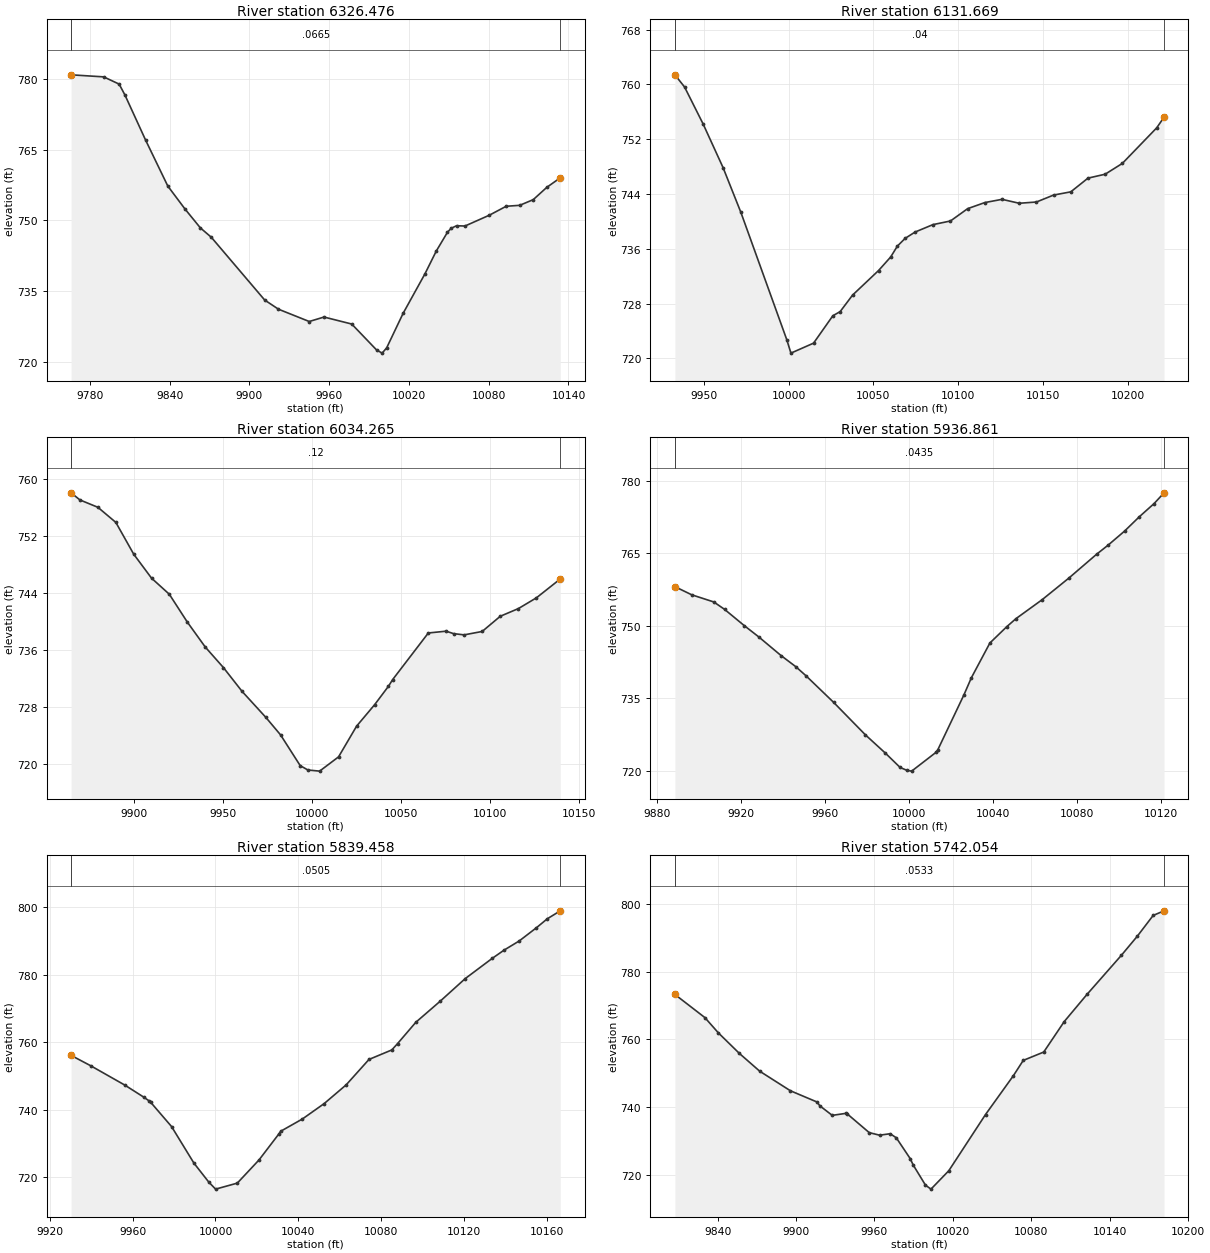
Type RM Length L Ch R = 1 ,6326.476,194.807200,194.807200,194.807200
XS GIS Cut Line= 6
771503.434453996810075.256479991771552.013422798810102.982178426
771601.137802176810147.269379852771649.136097769810242.264547945
771674.511020452810263.405207196771775.011694723810291.857485269
#Sta/Elev= 30
9765.825780.97319790.274780.53999801.952778.99959806.365776.6517 9821.82767.1139
9838.554757.32029851.439752.45549863.048748.42399871.294746.42559911.454733.0738
9921.827731.12449944.964728.51019956.093729.45819976.928727.97169995.611 722.464
9999.812721.784110003.21722.901110015.56730.228910032.02738.648310040.57743.5098
10048.97747.493510051.69 748.32410055.79748.876410062.13 748.81610080.41751.1127
10093.13753.016510103.31753.2196 10113.5754.428210123.68757.038710133.82 759.072
#Mann= 3 , 0 , 0
9765.825  0.0665       09765.825  0.0665       010133.82  0.0665       0
#XS Ineff= 2 , 0
       0                               0
Bank Sta=9765.825,10133.82
Exp/Cntr=0.3,0.1

Type RM Length L Ch R = 1 ,6131.669,97.403600,97.403600,97.403600
XS GIS Cut Line= 6
771519.466103542810333.001657644771561.825469998810308.966389475
771591.424689467 810276.49997124 771601.61692187810271.493362712
771650.393600702810291.616559449 771779.24928626810312.816383967
#Sta/Elev= 30
9933.019761.41129938.726759.63169949.613754.25719961.412 747.8639971.937741.3096
    9999 722.70610001.43720.759310014.77722.216210026.15726.218810030.46726.8248
10037.78729.239210053.11732.827910060.25734.8057 10064.2736.395110068.78737.5253
10074.68738.451710085.16  739.5310095.49740.061310105.62741.861810115.76742.7528
10125.89 743.22410136.02742.650310146.16742.832610156.29743.847810166.43744.3176
10176.56746.3195 10186.7746.894710196.83748.4717 10217.1753.671610221.41755.2196
#Mann= 3 , 0 , 0
9933.019    0.04       09933.019    0.04       010221.41    0.04       0
#XS Ineff= 2 , 0
       0                               0
Bank Sta=9933.019,10221.41
Exp/Cntr=0.3,0.1

Type RM Length L Ch R = 1 ,6034.265,97.403700,97.403700,97.403700
XS GIS Cut Line= 6
771520.171976292810372.326216777771550.492882441810377.089703695
771600.248031921810374.163589127771663.725867627810349.096152708
771692.639776135810343.940387812771788.163844182810356.907305613
#Sta/Elev= 30
9864.392 758.037 9869.33757.04149879.437756.00729889.544753.88539899.603749.4209
9909.605746.06379919.607743.80469929.699739.90919939.795736.40419950.065733.5033
9960.527730.17089973.915726.51659982.161724.0675  9993.2 719.7569997.528719.1396
10004.12 718.98310014.77720.985210024.92725.298510035.08 728.31410042.84730.8975
 10045.2731.833510065.24  738.3710075.25738.620810079.43738.278510085.36738.1035
10095.53738.5827 10105.7740.715910115.87741.791410126.04743.305810139.43745.9487
#Mann= 3 , 0 , 0
9864.392    0.12       09864.392    0.12       010139.43    0.12       0
#XS Ineff= 2 , 0
       0                               0
Bank Sta=9864.392,10139.43
Exp/Cntr=0.3,0.1

Type RM Length L Ch R = 1 ,5936.861,97.403600,97.403600,97.403600
XS GIS Cut Line= 6
771517.293352578810374.821023996771565.551615411810391.584243632
771577.963954668810399.529158046771590.210652583810411.141712496
771650.677398333 810492.88806663771683.379075028 810528.29645192
#Sta/Elev= 30
  9888.6758.09259896.647756.40199907.088754.93189912.225753.39979921.565750.0482
9928.405747.73239939.135743.83299946.063741.56069950.945739.67479964.161734.1438
9979.241727.44249988.768723.65419995.735720.7086    9999720.109210001.22719.9528
10012.73 723.81410013.63724.345910026.03735.673910029.63739.268110038.44746.4499
10046.53749.848110050.84751.482110063.24755.382910075.84759.811810089.17764.7887
 10094.7766.688210102.49769.581410109.56772.566810116.53775.271310121.26777.4917
#Mann= 3 , 0 , 0
  9888.6  0.0435       0  9888.6  0.0435       010121.26  0.0435       0
#XS Ineff= 2 , 0
       0                               0
Bank Sta=9888.6,10121.26
Exp/Cntr=0.3,0.1

Type RM Length L Ch R = 1 ,5839.458,97.403600,97.403600,97.403600
XS GIS Cut Line= 6
771482.458234095 810405.01146002771503.770359818810432.734457738
771533.894145906810522.515221245771545.425860839810547.507216787
771560.502123397810571.972702216771593.305928374810609.297483086
#Sta/Elev= 29
 9930.36756.11459939.747753.06929956.217747.3353 9965.53743.69489967.982742.6326
9968.749742.21549978.802735.03519989.582724.21039996.771718.564310000.06716.4857
10010.53718.2672   10021725.135810030.43732.726510031.48733.643210041.95 737.283
10052.43741.836610063.04747.386210074.05754.920410085.06757.736110087.82759.6038
10096.63765.923610108.37772.164710120.49778.888410133.49784.870510139.27787.3402
10146.48790.0171 10154.8793.935910160.05796.599110166.32798.9634
#Mann= 3 , 0 , 0
 9930.36  0.0505       0 9930.36  0.0505       010166.32  0.0505       0
#XS Ineff= 2 , 0
       0                               0
Bank Sta=9930.36,10166.32
Exp/Cntr=0.3,0.1

Type RM Length L Ch R = 1 ,5742.054,97.403600,97.403600,97.403600
XS GIS Cut Line= 6
 771262.84117068810427.884026474771310.585422654810440.359159283
771356.557225094810458.967176911771393.089780009810480.422896759
771479.266729168810560.193180524  771571.8271593810628.612922902
#Sta/Elev= 30
9807.342 773.2399830.244766.4106 9840.58 761.8869856.689755.79429872.239750.5393
 9895.71 744.7599916.075741.43399918.196740.31339927.672737.49069937.943 738.073
9939.269737.88989955.987732.38279963.891  731.639972.015732.05769976.687730.8527
  9987.3724.71019989.601722.8169    9999716.8571 10003.2715.678910016.83721.1193
10044.92737.740710066.25749.235310073.78753.743410089.45756.214110105.12765.2221
10122.54773.260810148.78784.796610160.96790.437410173.14 796.60610181.45797.9676
#Mann= 3 , 0 , 0
9807.342  0.0533       09807.342  0.0533       010181.45  0.0533       0
#XS Ineff= 2 , 0
       0                               0
Bank Sta=9807.342,10181.45
Exp/Cntr=0.3,0.1

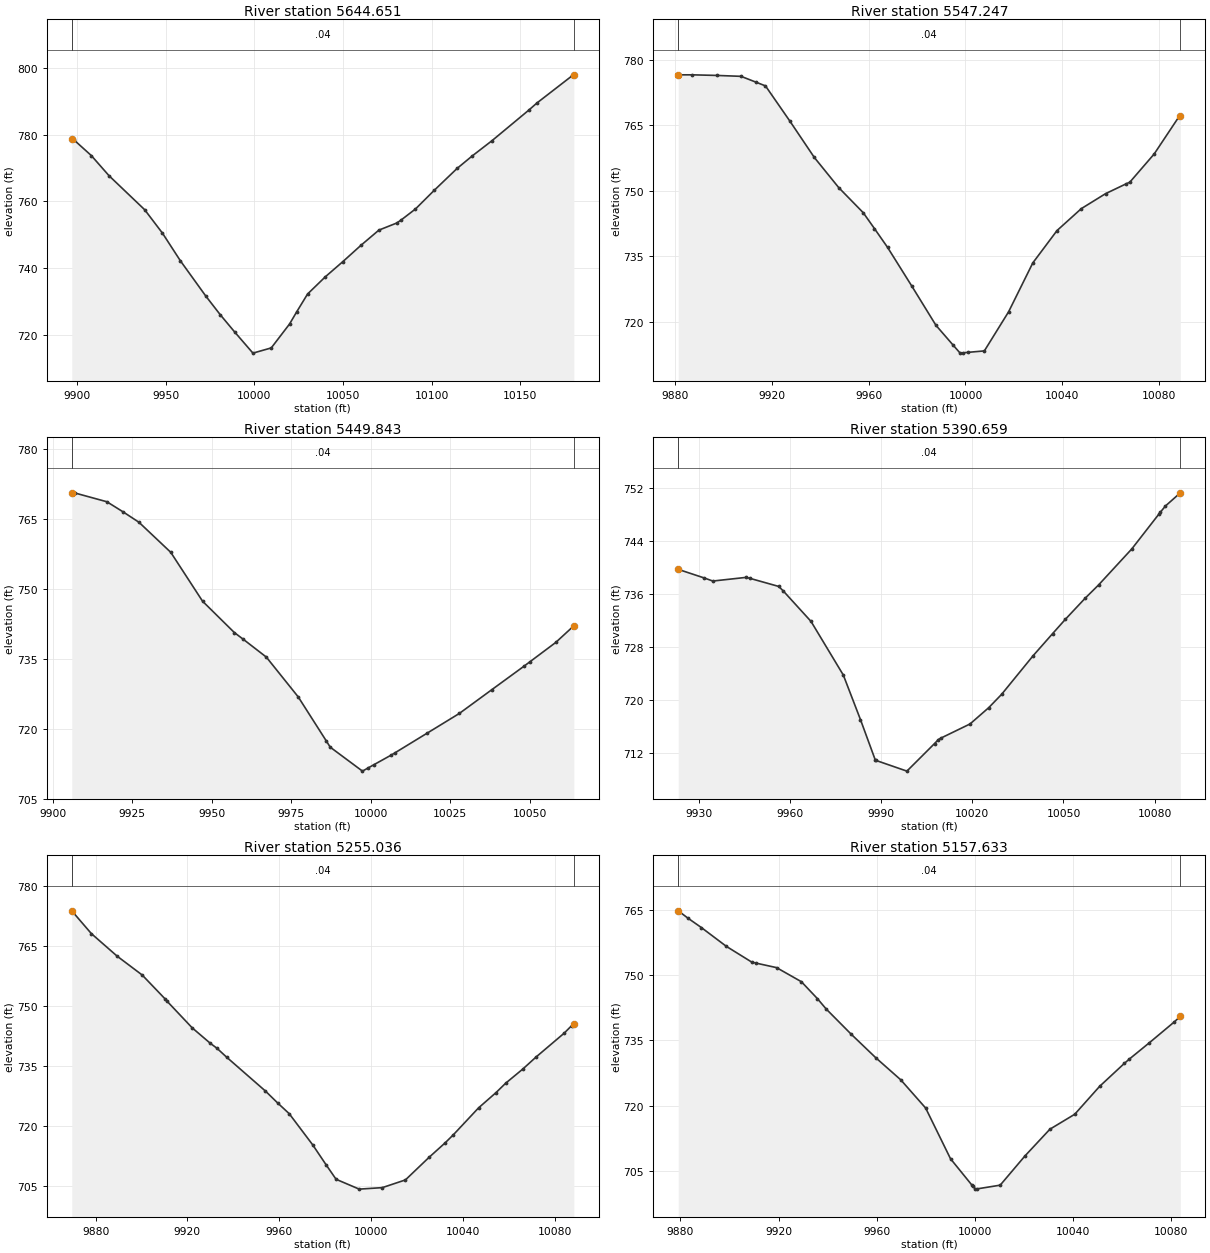
Type RM Length L Ch R = 1 ,5644.651,97.403600,97.403600,97.403600
XS GIS Cut Line= 6
771294.019049867810613.078414053771346.715465273810608.744461313
 771444.84292191810590.516728279771474.514984047810594.069841543
771509.232783334810605.664143477771565.752471733810635.169985646
#Sta/Elev= 30
9897.071778.81229898.055  778.559908.089773.73689918.123 767.662 9938.19757.4765
9948.224750.44169958.345742.13899972.615731.59489980.747726.00599988.914720.7962
9999.246714.432410009.58 715.99710019.91723.179310023.86726.765510030.06 732.172
 10040.1737.352310049.98741.905110060.21746.813910070.28751.352810080.38753.4909
 10082.8754.379210090.92757.699810101.46 763.27910114.37769.856810122.91773.6115
10134.09778.203210154.73787.324310159.38789.494110179.38797.729410180.24797.9661
#Mann= 3 , 0 , 0
9897.071    0.04       09897.071    0.04       010180.24    0.04       0
#XS Ineff= 2 , 0
       0                               0
Bank Sta=9897.071,10180.24
Exp/Cntr=0.3,0.1

Type RM Length L Ch R = 1 ,5547.247,97.403700,97.403700,97.403700
XS GIS Cut Line= 6
771309.283005571810699.478163347771389.615877707810688.202925092
771422.086763634 810687.05643727771428.197304811810687.274259668
771493.351497416810691.061124726771515.719436921 810693.90441783
#Sta/Elev= 29
9881.274776.49089887.047776.49179897.145776.35439907.243776.14529913.493774.7934
9917.341773.95589927.439765.88069937.537 757.5639947.635750.65349957.733744.9313
9962.394741.28159967.782736.99869977.788728.14589987.794719.14469994.886714.6119
  9997.8712.7685    9999712.8353   10001712.944610007.81713.277210017.83722.2286
10027.85733.435810037.86740.842110047.88745.8504 10057.9 749.27810066.26751.4908
10067.93751.901810078.01 758.37110088.09766.766510088.81767.1584
#Mann= 3 , 0 , 0
9881.274    0.04       09881.274    0.04       010088.81    0.04       0
#XS Ineff= 2 , 0
       0                               0
Bank Sta=9881.274,10088.81
Exp/Cntr=0.3,0.1

Type RM Length L Ch R = 1 ,5449.843,59.184300,59.184300,59.184300
XS GIS Cut Line= 6
771324.088469763810783.282677662771340.001865237810780.808740691
771377.765634875810779.304602972771403.845623101 810781.57207937
771466.867306543810792.320045788771480.678131708810793.056132424
#Sta/Elev= 25
9906.011770.59179906.934770.56879917.054 768.6769922.116766.52219927.118764.2866
9937.126757.83759947.134747.34349957.142740.6141 9959.91739.19499967.171735.3677
9977.209726.82199986.088717.31999987.259  716.05  9997.4710.9114    9999711.5272
   10001  712.2910006.41714.342810007.55714.808110017.69719.036310027.84723.2745
10037.98728.334910048.13733.385210050.02734.351210058.16 738.50610063.85742.0763
#Mann= 3 , 0 , 0
9906.011    0.04       09906.011    0.04       010063.85    0.04       0
#XS Ineff= 2 , 0
       0                               0
Bank Sta=9906.011,10063.85
Exp/Cntr=0.3,0.1

Type RM Length L Ch R = 1 ,5390.659,135.622900,135.622900,135.622900
XS GIS Cut Line= 6
771344.675976877810868.596301436771366.160734457810858.673769847
771400.304089752810846.387239737771461.142348421810829.328184938
771493.108073744810815.286813343 771499.17616792810811.567435821
#Sta/Elev= 30
9923.271739.76229923.628739.65569931.848738.41069934.643 737.9519945.658738.5043
9946.936738.3467 9956.33737.13779957.786736.47819966.958731.86739977.586723.7853
9983.223717.07679988.104710.98339988.308 710.9369998.498709.321410007.58713.4689
10008.88714.081310009.58714.273510019.26716.424810025.41718.876910029.64720.8796
10040.03726.711110046.41730.021310050.62732.184210057.17735.377910061.54737.3565
10072.47742.783710081.32747.988910081.87748.312910083.54749.250310088.44 751.237
#Mann= 3 , 0 , 0
9923.271    0.04       09923.271    0.04       010088.44    0.04       0
#XS Ineff= 2 , 0
       0                               0
Bank Sta=9923.271,10088.44
Exp/Cntr=0.3,0.1

Type RM Length L Ch R = 1 ,5255.036,97.403600,97.403600,97.403600
XS GIS Cut Line= 6
771437.586964817811062.565817192771462.763448216811007.728056328
 771472.05772794810979.863777412771483.632369873810911.644168349
771501.295909499810878.659748413 771515.62168228810861.755242455
#Sta/Elev= 30
9869.615773.71999878.158768.01769889.428762.35869900.312 757.6549910.332751.6494
9911.196751.0676 9922.08744.44639929.995740.56919932.871739.34059937.064737.1225
9953.954728.65399959.369725.62589964.354722.97029974.603715.16139980.451710.1636
9984.778706.55999994.853704.094410004.91704.469310014.99706.398510025.23712.0181
10032.18715.609410035.87717.691910046.84724.414210054.49 728.25910058.69730.6052
10066.21734.174310071.94737.161910084.11743.089410087.41744.992610088.37745.4472
#Mann= 3 , 0 , 0
9869.615    0.04       09869.615    0.04       010088.37    0.04       0
#XS Ineff= 2 , 0
       0                               0
Bank Sta=9869.615,10088.37
Exp/Cntr=0.3,0.1

Type RM Length L Ch R = 1 ,5157.633,97.403600,97.403600,97.403600
XS GIS Cut Line= 5
771554.113592212811074.177749434771561.053326487811043.177384729
771575.023795105810956.140928699771575.356215449810954.168747999
771588.228406352810872.510907098
#Sta/Elev= 29
9879.082764.87669883.139763.14569888.487761.03199898.734756.67189908.982753.0793
9910.849752.81979919.132751.7902 9929.26748.54299935.752744.66439939.388742.2416
9949.516736.46679959.644730.98249969.772  725.92  9979.9719.42559990.028707.7453
 9998.85701.5957    9999701.495710000.16700.7397   10001700.808210010.28701.6552
10020.41708.414310030.53714.548410040.65717.993810050.78724.4189 10060.9729.7336
10062.93730.725510071.02734.454810081.15739.242110083.67740.5575
#Mann= 3 , 0 , 0
9879.082    0.04       09879.082    0.04       010083.67    0.04       0
#XS Ineff= 2 , 0
       0                               0
Bank Sta=9879.082,10083.67
Exp/Cntr=0.3,0.1