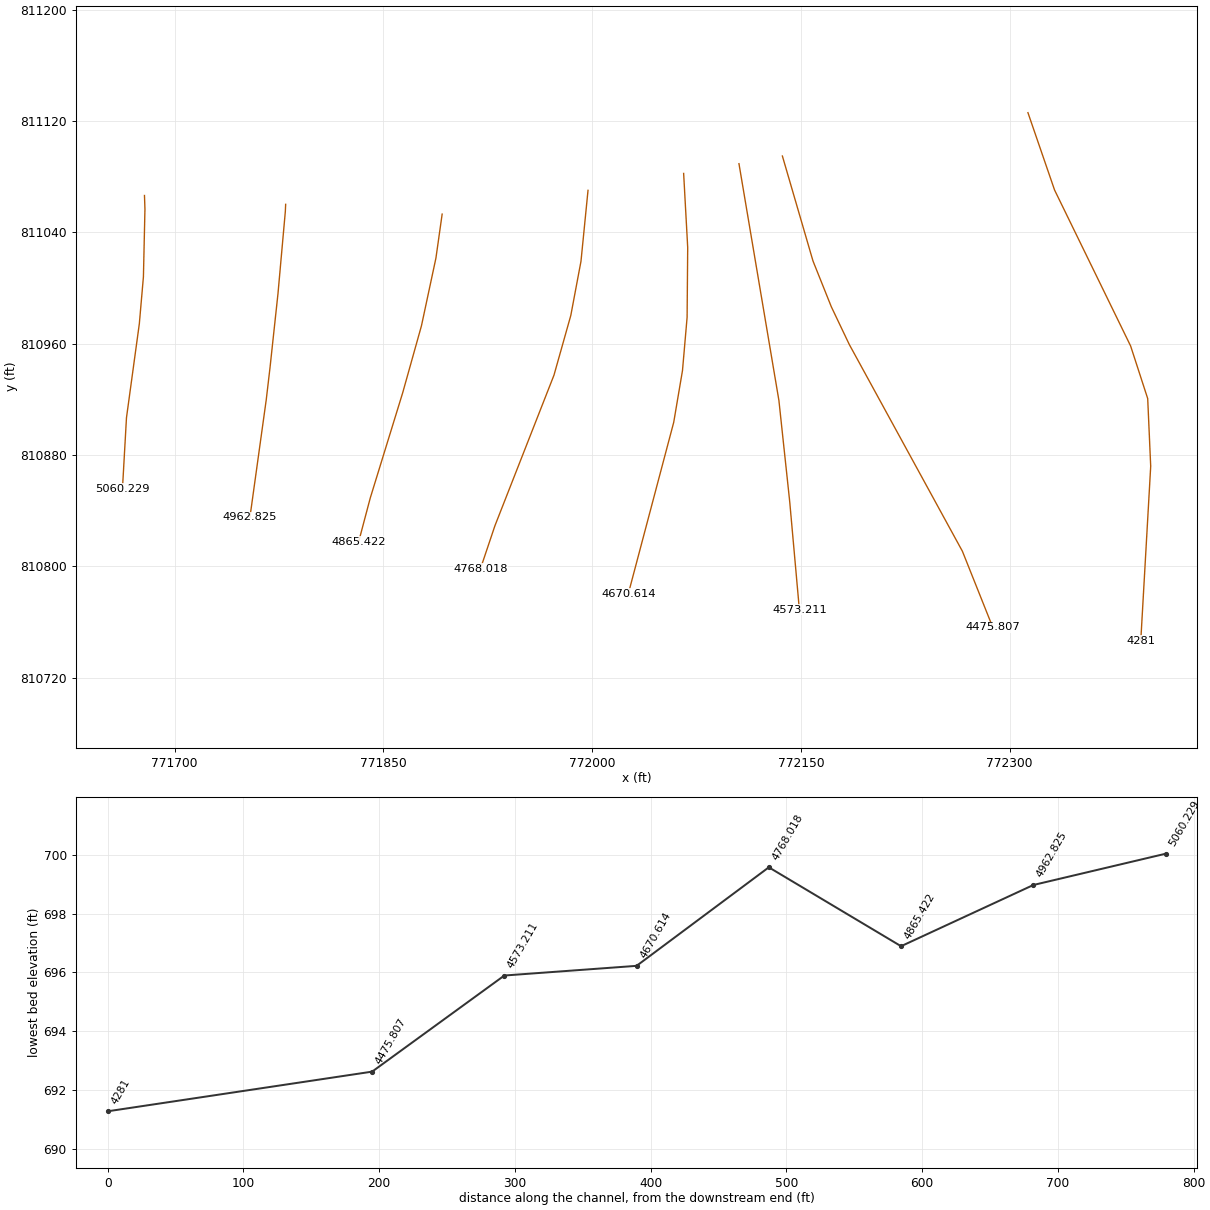
HEC-RAS study 17730_ras.prj: 17730

--- 17730_ras.g01 (geometry) --- (continued)

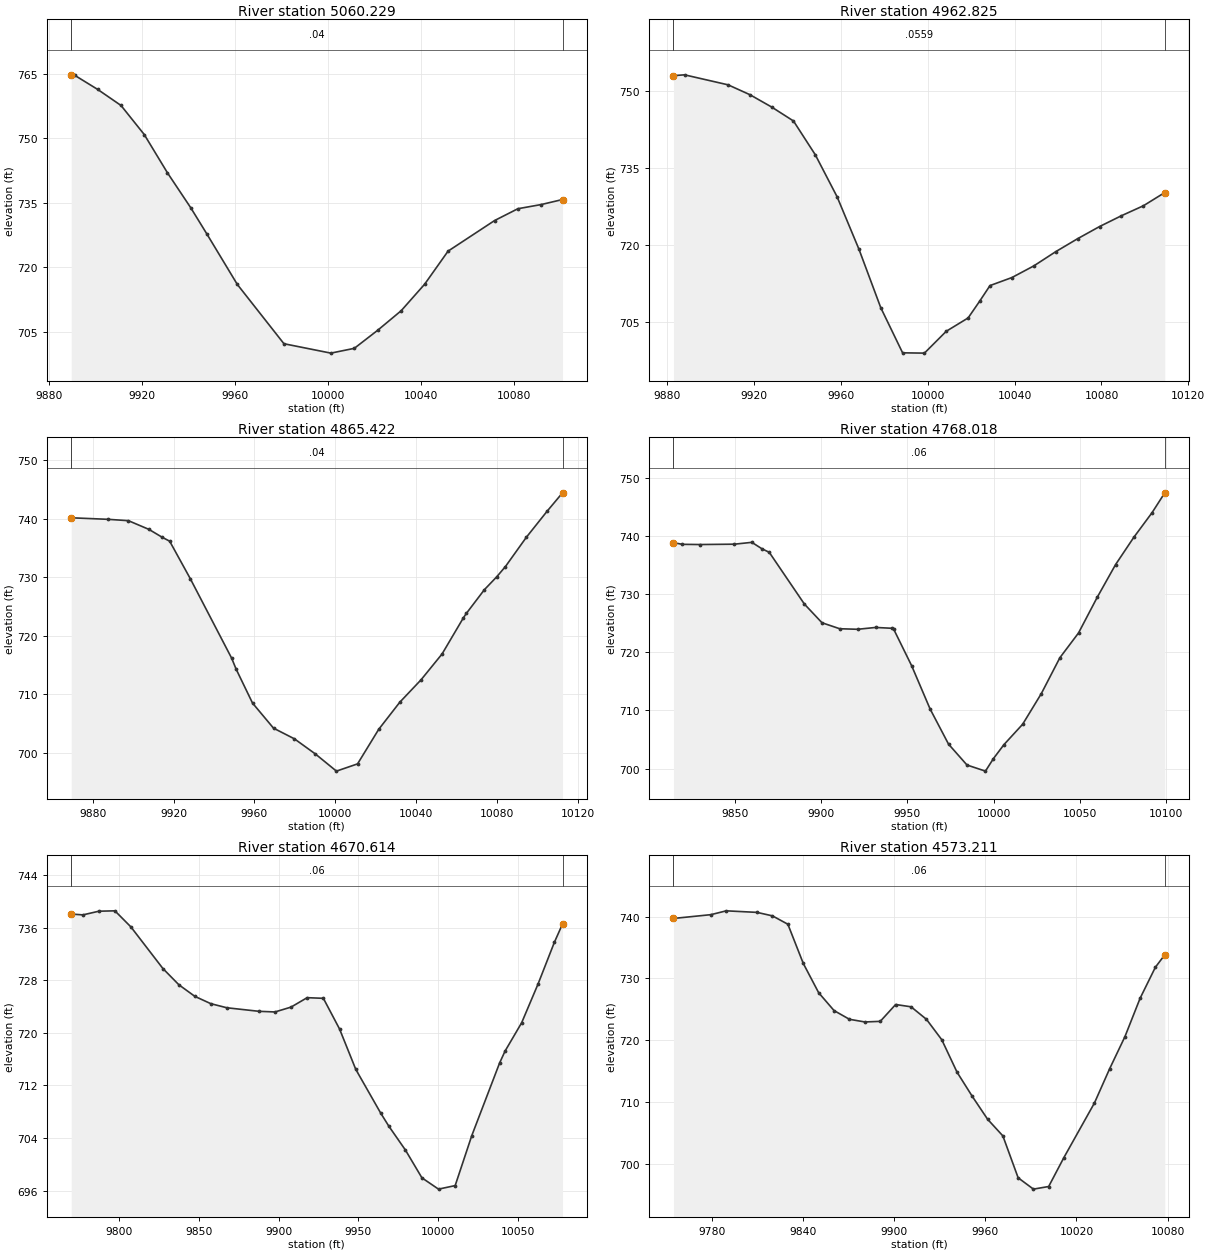
Type RM Length L Ch R = 1 ,5060.229,97.403700,97.403700,97.403700
XS GIS Cut Line= 6
771678.263206162811066.418398561 771678.60390286811056.595059746
771677.509113608811008.012234132771674.571541771810974.281974693
771665.328920093810906.695006678771662.454308131810855.828212559
#Sta/Elev= 20
9889.531 764.7599890.951 764.6729900.956761.35019910.959757.63229920.961750.8733
9930.964741.95639940.966733.84919947.956727.70899961.017716.01079981.093702.2168
10001.29700.031910011.38701.146310021.47705.360310031.56709.896710041.65716.0596
10051.73723.750310071.77730.871310081.79733.617710091.82734.5874   10101735.7565
#Mann= 3 , 0 , 0
9889.531    0.04       09889.531    0.04       0   10101    0.04       0
#XS Ineff= 2 , 0
       0                               0
Bank Sta=9889.531,10101
Exp/Cntr=0.3,0.1

Type RM Length L Ch R = 1 ,4962.825,97.403600,97.403600,97.403600
XS GIS Cut Line= 6
771779.721996269811060.077224179771779.495424895811054.956386013
771774.222031178810996.018170474771768.455249821810942.443325554
771765.787084418810919.723622973771754.061993141810835.238863157
#Sta/Elev= 24
9882.816752.96799887.898753.12719907.978751.17889918.018749.26139928.058746.8559
9938.098744.1432 9948.14737.57639958.197729.39239968.255 719.1999978.313707.8122
9988.371699.02799998.428698.968510008.49703.222210018.56705.816110023.88709.0767
10028.64712.114210038.74713.676810048.84 715.94610058.93718.713510069.03721.2424
10079.12723.602810089.22 725.71110099.32727.644710109.17730.2202
#Mann= 3 , 0 , 0
9882.816  0.0559       09882.816  0.0559       010109.17  0.0559       0
#XS Ineff= 2 , 0
       0                               0
Bank Sta=9882.816,10109.17
Exp/Cntr=0.3,0.1

Type RM Length L Ch R = 1 ,4865.422,97.403600,97.403600,97.403600
XS GIS Cut Line= 6
771892.194971883811053.047663203771887.728928961811021.477293423
 771877.33046688810972.826196244771863.826809765810924.610681687
771840.560475299810849.142886643771832.217914202810817.672874382
#Sta/Elev= 27
9869.294740.15839887.522739.89719897.621739.66329907.803738.17139914.235 736.849
9918.029 736.1629928.254729.75079948.706 716.1879950.929 714.3129959.056708.5107
9969.439704.22859979.823 702.3999990.206699.810610000.59696.888110011.06698.1274
10021.52704.022110031.99708.665210042.45712.471210052.91716.907310063.38723.0294
 10064.9723.818610073.84727.875310079.97730.083610084.26731.8257 10094.6736.8185
10104.95741.301710112.53744.4225
#Mann= 3 , 0 , 0
9869.294    0.04       09869.294    0.04       010112.53    0.04       0
#XS Ineff= 2 , 0
       0                               0
Bank Sta=9869.294,10112.53
Exp/Cntr=0.3,0.1

Type RM Length L Ch R = 1 ,4768.018,97.403600,97.403600,97.403600
XS GIS Cut Line= 6
771997.022899911811070.134782532771991.970015763811019.177796468
771984.650156947810980.205131992771972.555372921810937.295272359
771930.120537247810829.087039744 771919.66375302810798.018923636
#Sta/Elev= 30
9814.583738.80799819.743738.52459829.792738.4892 9849.89738.55039859.939738.8674
9865.789737.7631 9870.04737.1507 9890.39728.25799900.565725.05419910.852724.0259
9921.241723.93419931.631724.24859941.014724.1062 9942.02 723.9839952.477 717.675
9963.161710.24629973.844 704.2059984.527700.6198 9995.21699.57089999.853701.7309
10005.96704.136410016.75707.622110027.53712.869710038.32719.0554 10049.1723.2992
10059.89729.403610070.58735.058910081.13 739.73510091.68743.962910099.05747.3706
#Mann= 3 , 0 , 0
9814.583    0.06       09814.583    0.06       010099.05    0.06       0
#XS Ineff= 2 , 0
       0                               0
Bank Sta=9814.583,10099.05
Exp/Cntr=0.3,0.1

Type RM Length L Ch R = 1 ,4670.614,97.403600,97.403600,97.403600
XS GIS Cut Line= 6
 772065.74159388 811082.26161088772068.660092037811029.078051642
772068.228159395810978.834502321772064.911594345810940.614019664
 772058.60009987810903.362067808772025.927310352810780.018870821
#Sta/Elev= 30
 9770.32738.07699777.615737.94839787.628738.50869797.639738.56619807.651 736.117
9827.669 729.784 9837.67727.3115 9847.67725.5491 9857.67724.43579867.671723.8153
9887.723723.27699897.761 723.1799907.798723.91539917.895725.35099928.037725.2533
 9938.18720.57689948.322714.43639963.934707.77449968.989705.7988 9979.34702.1769
 9989.69697.937810000.06696.220510010.48696.758910020.89704.372610038.27715.4084
 10041.7  717.2310052.07721.5354 10062.3727.414510072.53733.771310077.63736.5636
#Mann= 3 , 0 , 0
 9770.32    0.06       0 9770.32    0.06       010077.63    0.06       0
#XS Ineff= 2 , 0
       0                               0
Bank Sta=9770.32,10077.63
Exp/Cntr=0.3,0.1

Type RM Length L Ch R = 1 ,4573.211,97.403700,97.403700,97.403700
XS GIS Cut Line= 5
772105.500164893811089.277829295  772134.2143179810919.056565388
772141.839391962810847.671798548772142.037947225810845.681679002
772148.913715621810768.838288526
#Sta/Elev= 30
9754.583739.68779779.204740.30139789.345740.92219809.628740.66989819.769 740.105
 9829.91738.75319840.052732.41419850.193  727.679860.334724.78059870.475723.3716
9880.617722.93989890.758723.03769900.899725.7636 9911.04725.39339921.182723.3693
9931.289720.05759941.346 714.8079951.403710.88549961.459707.19929971.516704.5026
9981.573697.7259 9991.63695.891410001.68696.314610011.72701.0062 10031.8709.8182
10041.84715.373410051.88720.548710061.92726.787410071.96731.794110078.15733.8061
#Mann= 3 , 0 , 0
9754.583    0.06       09754.583    0.06       010078.15    0.06       0
#XS Ineff= 2 , 0
       0                               0
Bank Sta=9754.583,10078.15
Exp/Cntr=0.3,0.1

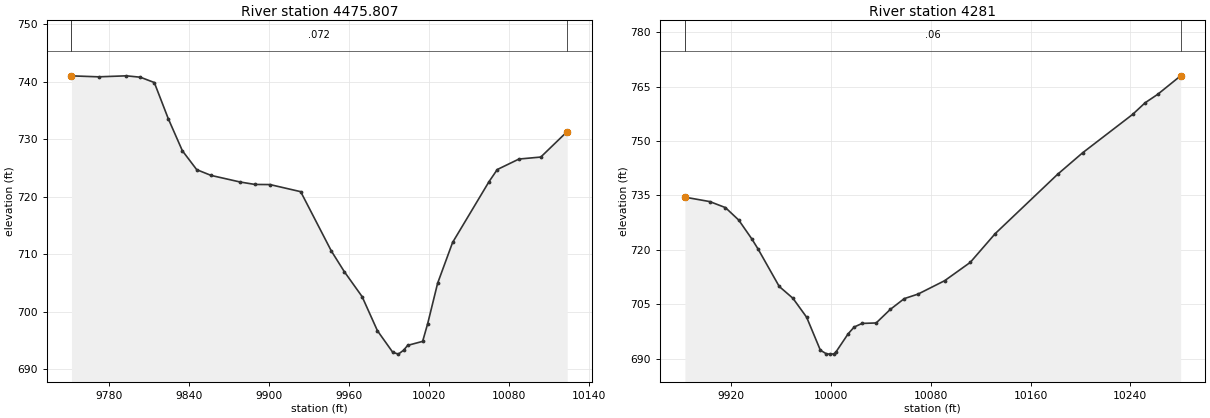
Type RM Length L Ch R = 1 ,4475.807,194.807200,194.807200,194.807200
XS GIS Cut Line= 6
772136.707415782811094.784991217772158.701199375811019.337947345
772171.905444511810986.378178525772184.763861372810959.388334168
772266.084124749810810.735892378772287.846246238810756.208058472
#Sta/Elev= 30
9751.571741.05959771.913740.89049792.833741.0644 9803.31740.82239813.787739.8979
9824.264733.61229834.869728.01919845.642724.72979856.414723.73129878.306722.5789
9889.383722.15869900.657722.13639923.709720.90019946.762710.56269956.401707.0006
9969.814702.6417 9981.34696.69359992.825692.95039997.052692.6232   10001693.3064
10004.03694.146510015.28694.8431 10019.1697.951710026.53704.958410037.78712.0636
10065.09722.629610071.33724.753410087.62726.5792   10104 726.92610123.84731.3646
#Mann= 3 , 0 , 0
9751.571   0.072       09751.571   0.072       010123.84   0.072       0
#XS Ineff= 2 , 0
       0                               0
Bank Sta=9751.571,10123.84
Exp/Cntr=0.3,0.1

Type RM Length L Ch R = 1 ,    4281,0.000000,0.000000,0.000000
XS GIS Cut Line= 6
772313.176616084811125.926614803772332.309561788 811070.35786963
772386.970022207810958.270935026772399.242652865810920.470862416
772401.402530068810871.828566625772394.269277344810746.533237464
#Sta/Elev= 30
9882.718734.52849902.712733.30479915.245731.65039925.906728.21759936.568722.9411
9941.517720.18379958.398709.92079969.389706.6637 9980.38701.43669991.372692.3724
9996.188691.3603    9999 691.27510002.39691.332310004.09691.965310013.63696.8554
 10018.5 698.74510024.89699.735910036.16699.865410047.42703.583610058.68706.5703
10069.77707.822810091.11711.515910111.59716.547310131.68724.497210181.72740.8407
10201.75746.754910241.82757.321610251.84760.524510261.85762.831410280.35767.9586
#Mann= 3 , 0 , 0
9882.718    0.06       09882.718    0.06       010280.35    0.06       0
#XS Ineff= 2 , 0
       0                               0
Bank Sta=9882.718,10280.35
Exp/Cntr=0.3,0.1